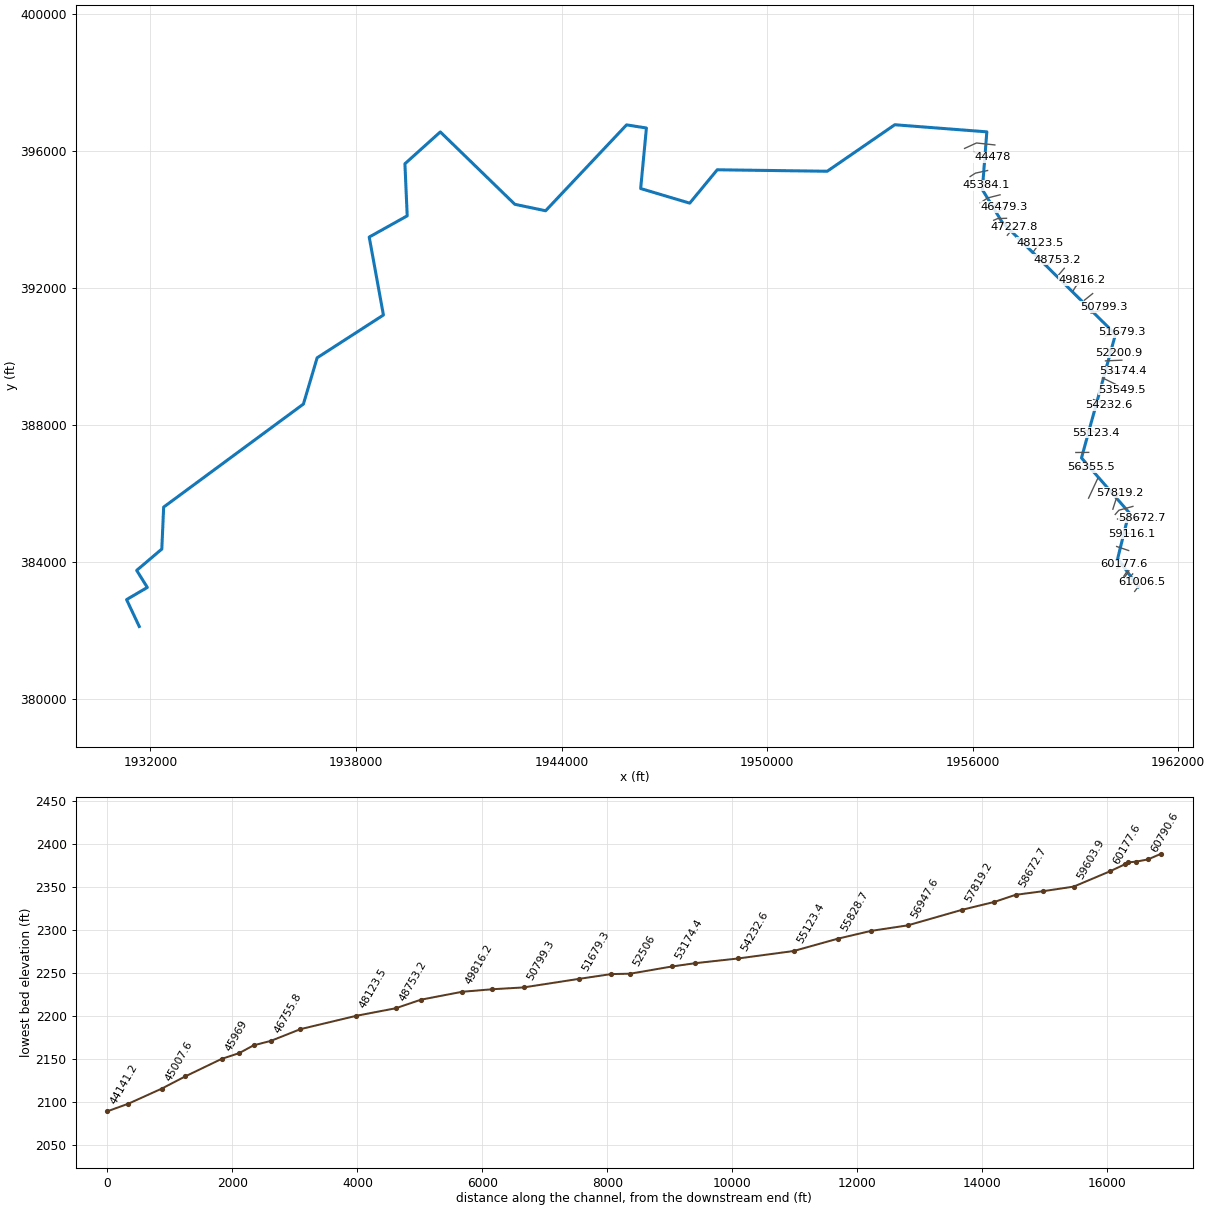
--- MUDDYCK2.prj (project) ---

Proj Title=MUDDYCK2
Current Plan=p01
Default Exp/Contr=0,0
English Units
Geom File=g01
Flow File=f01
Plan File=p01
BEGIN DESCRIPTION:
END DESCRIPTION:
DSS Export Rating Curves= 0
DSS Export Rating Curve Sorted= 0
DSS Export Volume Flow Curves= 0
DXF OffsetX= 0
DXF OffsetY= 0
DXF ScaleX= 0
DXF ScaleY= 0

--- MUDDYCK2.p01 (plan) ---

Plan Title=Floodplain
Program Version=4.00
Geom File=g01
Flow File=f01
K Sum by GR=0
Std Step Tol=0.01
Critical Tol=0.01
Num of Std Step Trials=20
Max Error Tol=0.3
Flow Tol Ratio=0.001
Split Flow NTrial=30
Split Flow Tol=0.02
Split Flow Ratio=0.02
Log Output Level=0
Friction Slope Method=1
Unsteady Friction Slope Method=2
Unsteady Bridges Friction Slope Method=1
Global Log Level=0
CheckData=False
Run HTab=0
Run UNet=0
Run PostProcess=0
UNET Theta=0
UNET Theta Warmup=0
UNET ZTol=0
UNET ZSATol=0
UNET MxIter=0
UNET MaxInSteps=0
UNET DtIC=0
UNET DtMin=0
UNET MaxCRTS=0
UNET WFStab=0
UNET SFStab=0
UNET WFX=0
UNET SFX=0
UNET DSS MLevel=0
UNET DZMax Abort=0
UNET Convert EG Bridges=0
UNET Use Existing IB Tables=0
UNET Froude Limit=0
UNET Froude Power=0
Write IC File=0
Echo Input=False
Echo Output=False
Write Detailed=0

--- MUDDYCK2.f01 (steady flow) ---

Flow Title=NFF Regression Equation
Program Version=4.10
Number of Profiles= 1
Profile Names=P100yr
River Rch & RM=MUDDYCK2,Main            ,61006.5
709.4375
River Rch & RM=MUDDYCK2,Main            ,59116.1
720.1426
River Rch & RM=MUDDYCK2,Main            ,58672.7
780.1704
River Rch & RM=MUDDYCK2,Main            ,56355.5
830.0394
River Rch & RM=MUDDYCK2,Main            ,53174.4
 886.498
River Rch & RM=MUDDYCK2,Main            ,52506
1074.594
River Rch & RM=MUDDYCK2,Main            ,49816.2
1131.235
River Rch & RM=MUDDYCK2,Main            ,47227.8
 1180.56
River Rch & RM=MUDDYCK2,Main            ,46479.3
1231.543
River Rch & RM=MUDDYCK2,Main            ,44141.2
1254.992
River Rch & RM=MUDDYCK2,Main            ,42803.8
1524.654
River Rch & RM=MUDDYCK2,Main            ,41786.3
1694.625
River Rch & RM=MUDDYCK2,Main            ,40689.9
1860.558
River Rch & RM=MUDDYCK2,Main            ,36256.8
1935.128
River Rch & RM=MUDDYCK2,Main            ,35231.8
2372.151
River Rch & RM=MUDDYCK2,Main            ,32995.7
2395.018
River Rch & RM=MUDDYCK2,Main            ,25557.6
2515.685
River Rch & RM=MUDDYCK2,Main            ,20305.9
2674.353
River Rch & RM=MUDDYCK2,Main            ,16202.3
 2828.08
River Rch & RM=MUDDYCK2,Main            ,11813.1
2983.257
River Rch & RM=MUDDYCK2,Main            ,622.1
3194.336
Boundary for River Rch & Prof#=MUDDYCK2,Main            , 1
Up Type= 0
Dn Type= 1
Dn Known WS=1475.3
DSS Import GetInterval= 0
DSS Import GetPeak= 0
DSS Import FillOption= 0

--- MUDDYCK2.g01 (geometry) ---

Geom Title=USGS 10m DEM
Program Version=4.10

River Reach=MUDDYCK2        ,Main
Reach XY= 30
     1960835.079      383259.668     1960232.351      384092.076
     1960563.466      385435.252     1959175.661      387030.724
     1960167.208       390641.68     1956858.934      393919.001
     1956281.282      394870.238     1956412.273      396558.461
     1953725.611      396766.044      1951754.07      395407.203
     1948543.331      395450.014     1947740.101      394474.871
     1946308.076      394902.003     1946476.279      396670.817
     1945897.124      396762.564     1943533.584      394252.689
     1942635.147      394441.491     1940459.944      396556.515
     1939427.021      395625.661      1939493.92      394104.184
     1938384.541      393483.742     1938800.021      391206.343
     1936864.593      389955.672     1936463.963      388604.309
     1932384.644      385593.848     1932331.125      384367.874
      1931597.82      383744.876      1931908.15      383245.744
     1931302.357      382890.944     1931672.364      382105.625

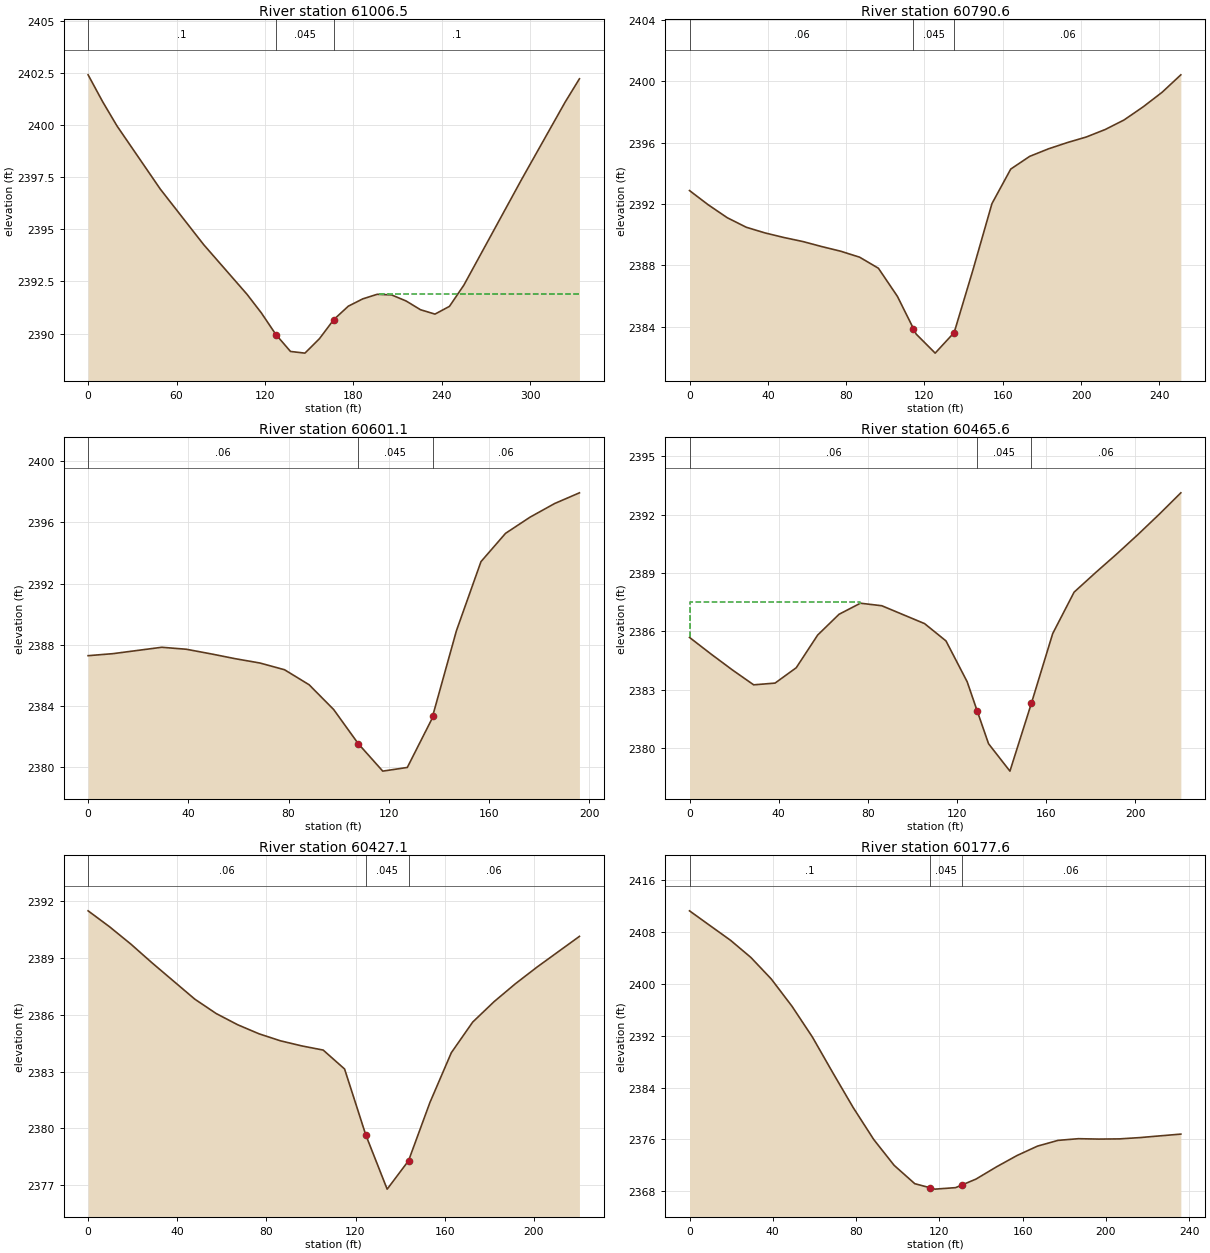
Type RM Length L Ch R = 1 ,61006.5 ,225.9,215.9,205.3
XS GIS Cut Line= 2
     1960728.655      383130.066     1960926.572      383398.295
#Sta/Elev= 24
       0  2402.4     9.8 2401.12    19.6 2399.95      49 2396.92    78.4 2394.26
   107.8 2391.88   117.6 2390.98   127.4 2389.95   137.3 2389.14   147.1 2389.06
   156.9 2389.75   166.7 2390.67   176.5 2391.31   186.3 2391.66   196.1 2391.88
   205.9 2391.85   215.7 2391.56   225.5 2391.14   235.3 2390.93   245.1  2391.3
   254.9 2392.32   294.1 2397.39   323.5 2401.08   333.3 2402.21
#Mann= 3 , 0 , 0
       0      .1       0   127.4    .045       0   166.7      .1       0
#XS Ineff= 2 , 0
                          197.18         2391.88
Permanent Ineff=
       F       F
Bank Sta=127.4,166.7
XS Rating Curve= 0 ,0
Exp/Cntr=0.3,0.1

Type RM Length L Ch R = 1 ,60790.6 ,181.3,189.5,197.8
XS GIS Cut Line= 2
     1960624.489      383369.649     1960840.635      383497.253
#Sta/Elev= 29
       0 2392.87     9.6 2391.94    19.3  2391.1      29 2390.48    38.6 2390.11
    48.3 2389.81    57.9 2389.55    67.6 2389.22    77.2 2388.92    86.9 2388.53
    96.5 2387.81   106.2 2385.98   114.4 2383.88   115.8 2383.52   125.5 2382.28
   129.4 2382.82   135.2 2383.62   144.8  2387.7   154.5 2392.02   164.1 2394.27
   173.8  2395.1   183.4 2395.59   193.1    2396   202.7 2396.36   212.4 2396.85
     222 2397.47   231.7 2398.32   241.4 2399.27     251 2400.41
#Mann= 3 , 0 , 0
       0     .06       0   114.4    .045       0   135.2     .06       0
Bank Sta=114.4,135.2
XS Rating Curve= 0 ,0
Exp/Cntr=0.3,0.1

Type RM Length L Ch R = 1 ,60601.1 ,132.6,135.5,137.8
XS GIS Cut Line= 2
      1960543.76      383489.441      1960668.76      383640.482
#Sta/Elev= 23
       0 2387.28     9.8 2387.41    19.6 2387.62    29.4 2387.83    39.2  2387.7
      49  2387.4    58.8 2387.08    68.6  2386.8    78.4 2386.36    88.2 2385.38
      98 2383.76   107.8 2381.53   117.6 2379.73   122.5 2379.85   127.4 2379.97
   137.2 2383.14   137.5 2383.32     147 2388.91   156.8 2393.43   166.6 2395.28
   176.4 2396.34   186.2 2397.23   196.1 2397.93
#Mann= 3 , 0 , 0
       0     .06       0   107.8    .045       0   137.5     .06       0
Bank Sta=107.8,137.5
XS Rating Curve= 0 ,0
Exp/Cntr=0.3,0.1

Type RM Length L Ch R = 1 ,60465.6 ,38.5,38.5,38.5
XS GIS Cut Line= 2
     1960438.725      383548.468     1960560.253      383732.496
#Sta/Elev= 26
       0 2385.68     9.6 2384.83    19.2 2384.01    28.8 2383.24    38.4 2383.33
    47.9 2384.12    57.5  2385.8    67.1 2386.87    76.7 2387.44    86.3 2387.31
    95.9 2386.85   105.5 2386.39   115.1  2385.5   124.6  2383.4   129.1  2381.9
   134.2 2380.21   143.8  2378.8   144.1 2378.91   153.4 2382.28     163 2385.88
   172.6 2388.01   182.2 2389.01   191.8 2389.98   201.4 2390.99     211 2392.04
   220.5 2393.12
#Mann= 3 , 0 , 0
       0     .06       0   129.1    .045       0   153.4     .06       0
#XS Ineff= 2 , 0
           76.41  2387.5
Permanent Ineff=
       F       F
Bank Sta=129.1,153.4
XS Rating Curve= 0 ,0
Exp/Cntr=0.3,0.1

Type RM Length L Ch R = 1 ,60427.1 ,258.7,249.5,240.1
XS GIS Cut Line= 2
     1960410.079       383574.51     1960531.607      383758.538
#Sta/Elev= 26
       0  2391.5     9.6 2390.66    19.2 2389.74    28.8 2388.74    38.4 2387.78
    47.9 2386.83    57.5 2386.07    67.1 2385.48    76.7    2385    86.3 2384.63
    95.9 2384.36   105.5 2384.14   115.1 2383.14   119.8 2381.42   124.6 2379.66
   134.2 2376.79   134.8 2376.88   143.8 2378.29   153.4 2381.37     163    2384
   172.6 2385.62   182.2  2386.7   191.8 2387.65   201.4 2388.52     211 2389.34
   220.5 2390.15
#Mann= 3 , 0 , 0
       0     .06       0   124.6    .045       0   143.8     .06       0
Bank Sta=124.6,143.8
XS Rating Curve= 0 ,0
Exp/Cntr=0.3,0.1

Type RM Length L Ch R = 1 ,60177.6 ,592.1,573.8,551.5
XS GIS Cut Line= 2
     1960212.162      383796.732     1960410.079      383925.205
#Sta/Elev= 27
       0  2411.3     9.8 2409.03    19.7 2406.75    29.5 2404.09    39.3 2400.76
    49.2 2396.57      59 2391.82    68.8 2386.31    78.6 2380.92    88.5 2375.97
    98.3 2371.98   108.2 2369.15   115.7 2368.51     118 2368.31   127.8 2368.54
   130.7 2368.93   137.6 2369.86   147.5 2371.76   157.3  2373.5   167.1 2374.95
     177 2375.84   186.8  2376.1   196.6 2376.04   206.5 2376.07   216.3 2376.27
   226.1 2376.54     236 2376.81
#Mann= 3 , 0 , 0
       0      .1       0   115.7    .045       0   130.7     .06       0
Bank Sta=115.7,130.7
XS Rating Curve= 0 ,0
Exp/Cntr=0.3,0.1

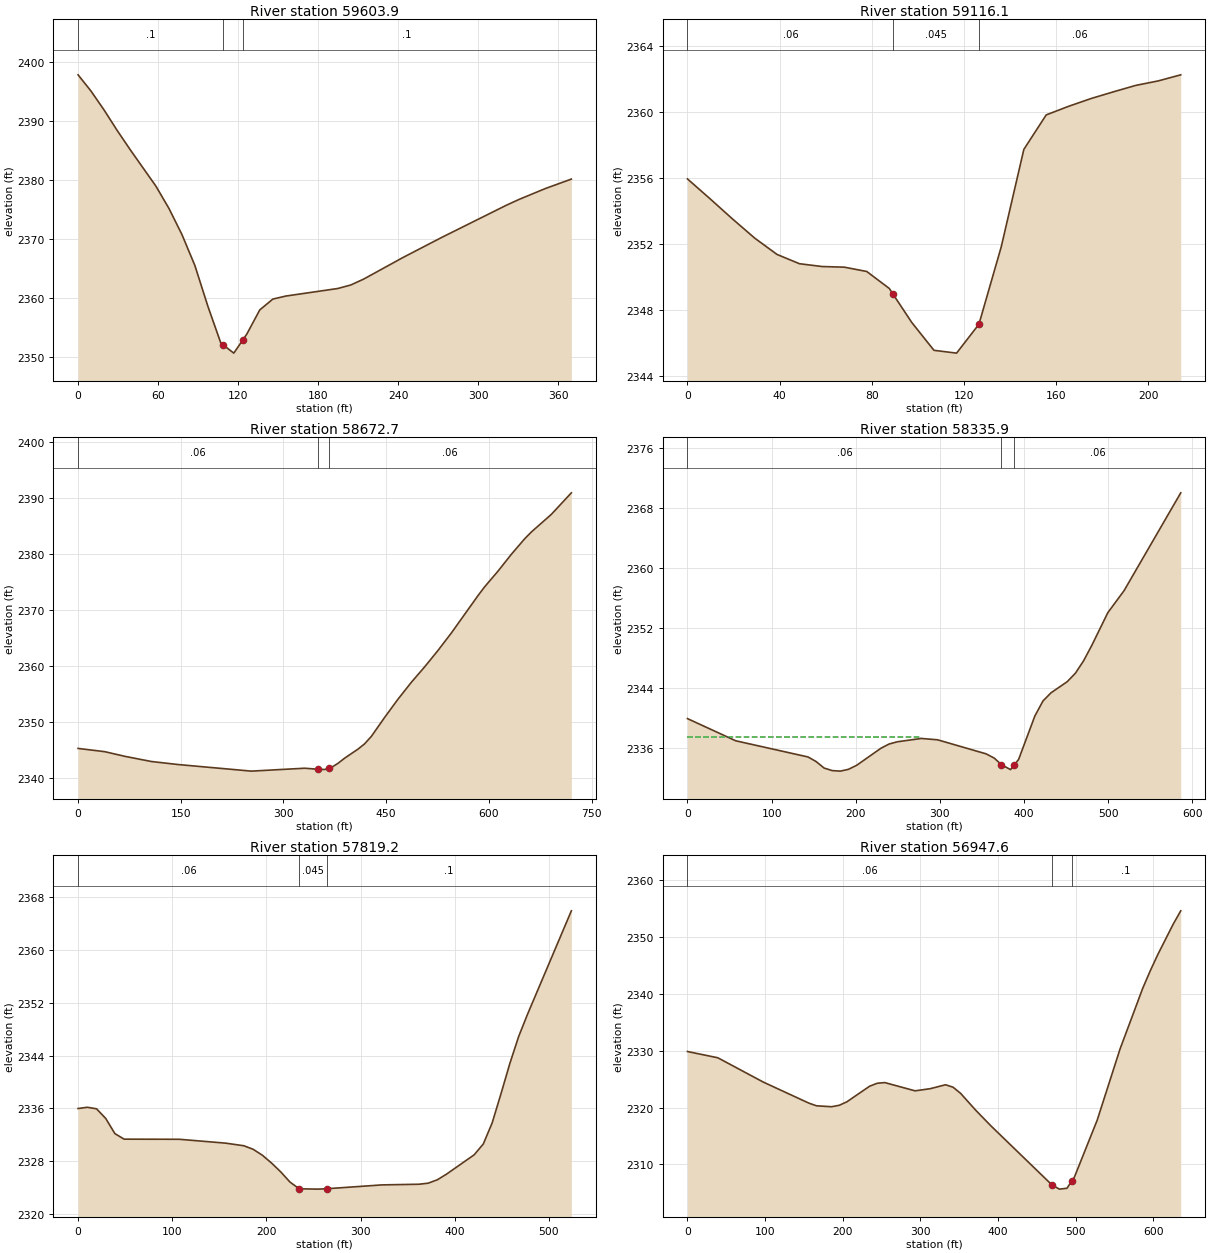
Type RM Length L Ch R = 1 ,59603.9 ,483.9,487.8,491.5
XS GIS Cut Line= 2
     1960201.746      384442.566      1960552.44       384324.51
#Sta/Elev= 27
       0 2397.82     9.7 2395.07    19.5 2391.87    29.2 2388.45      39 2385.18
    58.4 2378.97    68.2 2375.19    77.9 2370.79    87.6 2365.55    97.4 2358.62
   107.1  2352.4   108.7 2352.12   116.8 2350.71   123.7 2352.99   126.6 2353.95
   136.3 2358.03   146.1 2359.86   155.8 2360.37   194.8 2361.65   204.5 2362.24
   214.2 2363.24   243.4 2366.86   272.7 2370.29   321.3 2375.75   331.1 2376.76
   350.6 2378.58     370 2380.17
#Mann= 3 , 0 , 0
       0      .1       0   108.7    .045       0   123.7      .1       0
Bank Sta=108.7,123.7
XS Rating Curve= 0 ,0
Exp/Cntr=0.3,0.1

Type RM Length L Ch R = 1 ,59116.1 ,437,443.4,449.6
XS GIS Cut Line= 2
      1960431.78      384846.211     1960642.718      384809.753
#Sta/Elev= 25
       0 2355.95     9.7 2354.76    19.5 2353.53    29.2 2352.36    38.9 2351.37
    48.6 2350.81    58.4 2350.64    68.1  2350.6    77.8 2350.34    87.6 2349.31
    89.3 2348.95    97.3 2347.26   104.3 2346.03     107 2345.56   116.8 2345.39
   126.5 2347.14   136.2 2351.84     146 2357.74   155.7 2359.83   165.4 2360.35
   175.1 2360.82   184.9 2361.23   194.6 2361.62   204.3 2361.89   214.1 2362.26
#Mann= 3 , 0 , 0
       0     .06       0    89.3    .045       0   126.5     .06       0
Bank Sta=89.3,126.5
XS Rating Curve= 0 ,0
Exp/Cntr=0.3,0.1

Type RM Length L Ch R = 1 ,58672.7 ,333,336.7,340.3
XS GIS Cut Line= 2
     1960228.655      385244.649     1960948.273      385279.371
#Sta/Elev= 30
       0  2345.2    38.9 2344.62    68.2 2343.79   107.1 2342.86     146 2342.32
   253.1 2341.14     331 2341.66   351.1 2341.47   360.2 2341.43   366.1 2341.65
     370 2341.79   379.7 2342.54   389.4 2343.46   408.9 2345.08   418.6 2346.03
   428.4 2347.36   447.8 2350.75   467.3 2354.01   486.8 2357.03   506.3  2359.8
   525.7 2362.72   545.2 2365.84   584.2 2372.54   593.9 2374.11   613.4 2376.91
   632.8 2379.91   652.3 2382.69     662  2383.9   691.2 2387.05   720.5 2390.91
#Mann= 3 , 0 , 0
       0     .06       0   351.1    .045       0   366.1     .06       0
Bank Sta=351.1,366.1
XS Rating Curve= 0 ,0
Exp/Cntr=0.3,0.1

Type RM Length L Ch R = 1 ,58335.9 ,494.4,516.8,537
XS GIS Cut Line= 3
     1960160.554      385380.131     1960267.325      385502.526
     1960676.179      385614.506
#Sta/Elev= 30
       0 2339.95    57.3 2336.99   143.3 2334.83   152.9 2334.22   162.4 2333.35
   172.1 2333.01   181.7 2332.94   191.3 2333.18     201 2333.71   229.9 2335.99
   239.5 2336.55   249.1 2336.85     278  2337.3   297.3 2337.12   355.1 2335.24
   364.7 2334.67   373.1 2333.81     384 2333.14   388.1 2333.72   393.6  2334.5
   412.9  2340.3   422.6 2342.31   432.2  2343.4   451.4 2344.88   461.1 2346.01
   470.7 2347.64   480.4 2349.68   499.6 2354.08   518.9 2357.02   586.3 2370.08
#Mann= 3 , 0 , 0
       0     .06       0   373.1    .045       0   388.1     .06       0
#XS Ineff= 2 , 0
          278.03  2337.5
Permanent Ineff=
       F       F
Bank Sta=373.1,388.1
XS Rating Curve= 0 ,0
Exp/Cntr=0.3,0.1

Type RM Length L Ch R = 1 ,57819.2 ,870.1,871.5,868.6
XS GIS Cut Line= 3
     1960090.635      385532.843     1960222.579      385942.566
     1960285.079       386012.01
#Sta/Elev= 30
       0 2335.99     9.8 2336.18    19.6 2335.95    29.4 2334.48    39.1 2332.19
    48.9 2331.35   107.6 2331.33   156.5 2330.75   176.1 2330.35   185.9 2329.82
   195.7 2328.92   205.4 2327.74   215.2  2326.4     225 2324.86   234.8 2323.83
   254.4 2323.78   264.1 2323.84   322.8 2324.42     362 2324.52   371.8 2324.68
   381.5 2325.19   391.3 2326.05   420.7 2328.98   430.4 2330.63   439.8 2333.82
   449.1  2338.2   458.5 2342.78   467.8 2346.85   477.2 2350.22   523.9 2365.94
#Mann= 3 , 0 , 0
       0     .06       0   234.8    .045       0   264.1      .1       0
Bank Sta=234.8,264.1
XS Rating Curve= 0 ,0
Exp/Cntr=0.3,0.1

Type RM Length L Ch R = 1 ,56947.6 ,616.4,592.1,566.4
XS GIS Cut Line= 2
     1959382.301       385855.76     1959649.662      386432.149
#Sta/Elev= 30
       0 2329.84    39.1 2328.74    97.8 2324.46   156.4 2320.77   166.2  2320.3
   185.7 2320.14   195.5 2320.39   205.3    2321   234.6 2323.74   244.4 2324.26
   254.2 2324.38   293.2 2322.93   312.8 2323.31   332.4    2324   342.1 2323.57
   351.9 2322.48   371.4 2319.51     391 2316.76   469.2 2306.44     479 2305.66
   488.8 2305.81   494.7 2307.02   498.5  2307.8   527.8 2317.79   557.2 2330.28
   586.5 2340.98   596.3 2344.08     606 2346.92   625.6  2352.2   635.4 2354.56
#Mann= 3 , 0 , 0
       0     .06       0   469.2    .045       0   494.7      .1       0
Bank Sta=469.2,494.7
XS Rating Curve= 0 ,0
Exp/Cntr=0.3,0.1

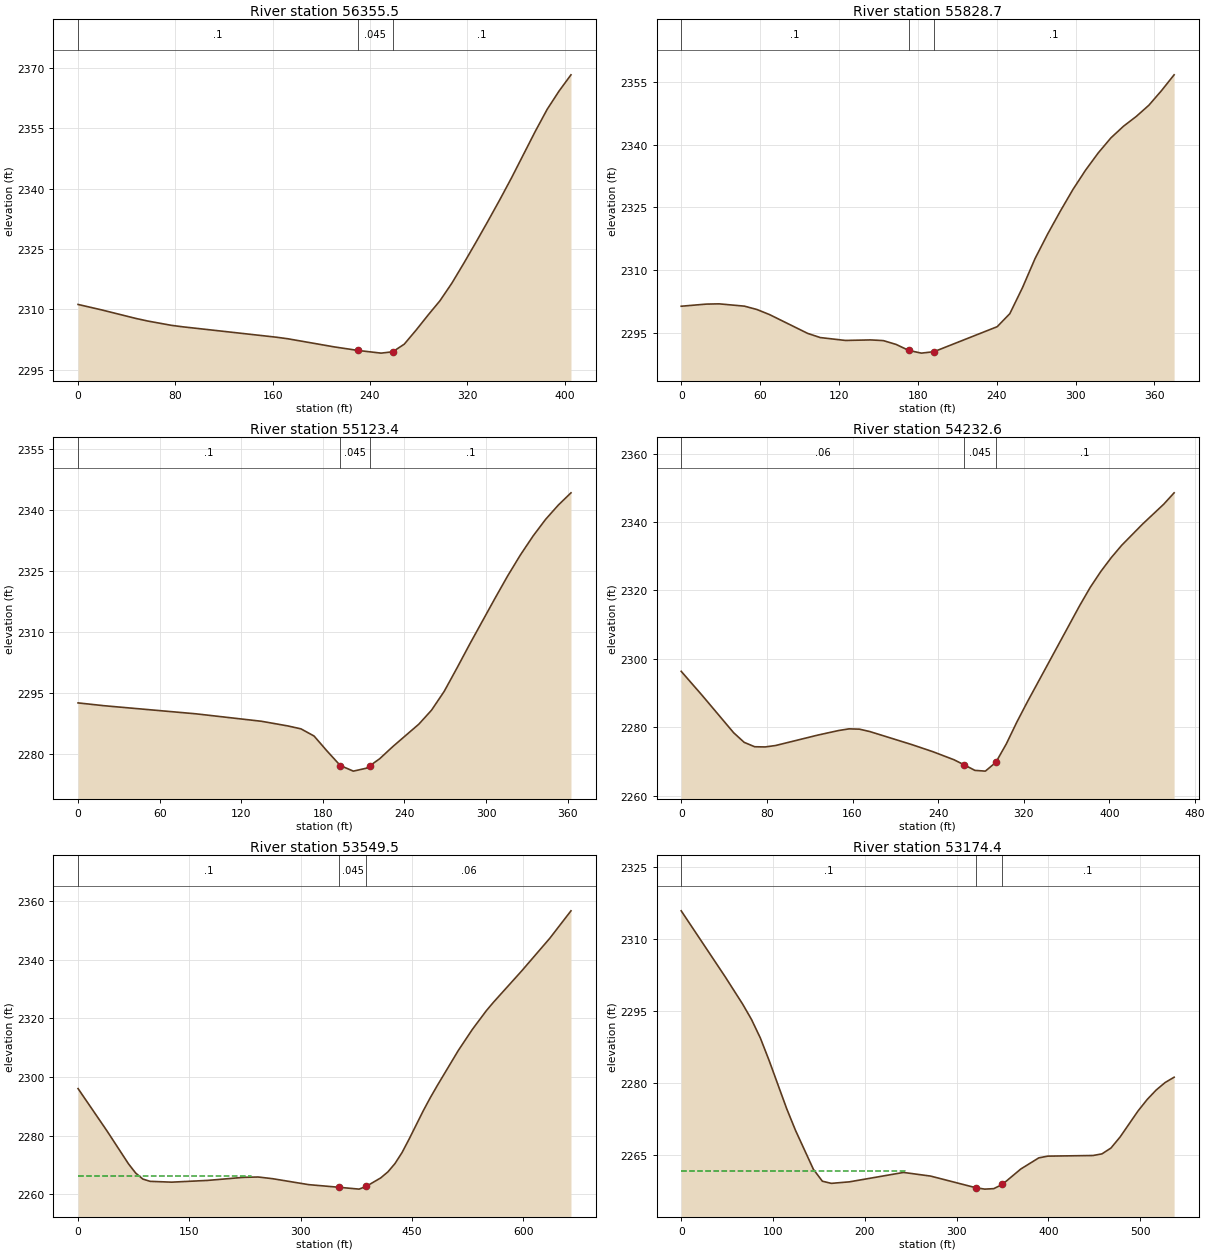
Type RM Length L Ch R = 1 ,56355.5 ,528.3,526.9,517.3
XS GIS Cut Line= 3
     1959058.991      386726.485     1959327.221      386723.881
     1959460.033      386757.735
#Sta/Elev= 26
       0 2311.24    19.2  2309.9    47.9 2307.74    57.5 2307.11    76.6 2306.06
    86.2 2305.68   162.9 2303.11   172.4 2302.72   210.8 2300.69   229.9 2299.83
   249.1 2299.15   258.7 2299.48   268.2 2301.37     278 2304.88   287.8  2308.6
   297.6 2312.17   307.4 2316.54   317.2 2321.48     327 2326.59   336.8 2331.81
   346.6 2337.15   356.4 2342.67   375.9  2354.2   385.7 2359.69   395.5 2364.24
   405.3 2368.27
#Mann= 3 , 0 , 0
       0      .1       0   229.9    .045       0   258.7      .1       0
Bank Sta=229.9,258.7
XS Rating Curve= 0 ,0
Exp/Cntr=0.3,0.1

Type RM Length L Ch R = 1 ,55828.7 ,706.8,705.2,703.6
XS GIS Cut Line= 2
     1959010.773      387189.093     1959385.773      387192.566
#Sta/Elev= 30
       0 2301.37    19.2 2301.88    28.8 2301.94    48.1 2301.39    57.7 2300.58
    67.3 2299.36    96.2 2294.88   105.8 2293.88     125 2293.19   144.2 2293.32
   153.8 2293.15   163.5 2292.24   173.1 2290.81   182.7 2290.16   192.3  2290.5
   240.4 2296.48     250 2299.59   259.6 2305.78   269.2 2312.76   278.9  2318.7
   288.5 2324.14   298.1 2329.32   307.7 2333.93   317.3 2338.03   326.9 2341.61
   336.6 2344.43   346.2 2346.74   355.8 2349.42   365.4 2352.91     375 2356.69
#Mann= 3 , 0 , 0
       0      .1       0   173.1    .045       0   192.3      .1       0
Bank Sta=173.1,192.3
XS Rating Curve= 0 ,0
Exp/Cntr=0.3,0.1

Type RM Length L Ch R = 1 ,55123.4 ,897.3,890.8,884.1
XS GIS Cut Line= 3
     1959253.829      387834.927     1959503.829      387817.566
     1959604.523      387768.955
#Sta/Elev= 26
       0 2292.62    19.3 2291.92    86.8 2289.93   134.9  2288.1   154.2 2286.96
   163.9 2286.24   173.5 2284.48   183.1 2280.78   192.8 2277.22   202.4 2275.85
     212 2276.57   214.7 2277.21   221.7 2278.88   231.3 2281.85   250.6 2287.41
   259.9 2290.84   269.2 2295.46   278.6  2301.2   287.9 2307.03   306.5  2318.3
   315.8  2323.8   325.1 2328.92   334.5 2333.62   343.8 2337.75   353.1 2341.24
   362.4 2344.25
#Mann= 3 , 0 , 0
       0      .1       0   192.8    .045       0   214.7      .1       0
Bank Sta=192.8,214.7
XS Rating Curve= 0 ,0
Exp/Cntr=0.3,0.1

Type RM Length L Ch R = 1 ,54232.6 ,685.2,683.1,674.9
XS GIS Cut Line= 2
     1959528.135      388734.232      1959958.69      388571.038
#Sta/Elev= 30
       0 2296.33    19.6 2289.29      49 2278.37    58.8 2275.57    68.6 2274.28
    78.4 2274.22    88.2 2274.64   127.4 2277.67     147 2279.02   156.8 2279.51
   166.5 2279.42   176.3 2278.71   215.5  2274.9   235.1 2272.83   254.7 2270.49
   264.5 2268.96   274.3 2267.37   284.1 2267.15   293.9 2269.72   303.7 2275.13
   313.5 2281.49   323.3 2287.38   372.3 2315.61   382.1  2320.9   391.9 2325.51
   401.7 2329.58   411.5  2333.2   431.1 2339.43   450.6 2345.16   460.4 2348.52
#Mann= 3 , 0 , 0
       0     .06       0   264.5    .045       0   293.9      .1       0
Bank Sta=264.5,293.9
XS Rating Curve= 0 ,0
Exp/Cntr=0.3,0.1

Type RM Length L Ch R = 1 ,53549.5 ,363,375.1,392.4
XS GIS Cut Line= 3
     1959788.551      389369.649     1960163.551      389185.621
     1960354.523      389029.371
#Sta/Elev= 30
       0 2296.04    38.9 2281.63      68 2270.34    77.7 2267.19    87.4 2265.14
    97.1 2264.37   126.3 2264.09   174.9 2264.69   223.4 2265.74   242.9 2265.85
   262.3 2265.27   310.9 2263.24   351.8 2262.34   378.9 2261.71   388.6 2262.67
     408 2265.54   417.7  2267.6   427.2 2270.43   436.7 2274.17   446.2 2278.75
   465.2 2288.39   474.7 2292.87   484.2 2297.05   512.6 2309.05   531.6 2316.27
   550.6 2322.71   560.1 2325.55     598 2336.21     636 2347.39   664.5 2356.75
#Mann= 3 , 0 , 0
       0      .1       0   351.8    .045       0   388.6     .06       0
#XS Ineff= 2 , 0
          233.66 2266.34
Permanent Ineff=
       F       F
Bank Sta=351.8,388.6
XS Rating Curve= 0 ,0
Exp/Cntr=0.3,0.1

Type RM Length L Ch R = 1 ,53174.4 ,668.6,668.4,461.4
XS GIS Cut Line= 3
     1959868.412      389595.343     1959993.412      389546.732
      1960396.19      389557.149
#Sta/Elev= 30
       0 2315.88    47.9 2302.13    67.1 2296.38    76.6 2293.22    86.2 2289.37
    95.8 2284.66     115 2274.58   124.5 2270.11     144 2261.98   153.8 2259.49
   163.6 2259.04   183.3 2259.36   242.2 2261.32   271.7 2260.56   320.8 2258.14
   330.7 2257.84   340.5 2257.94  349.862258.819     370 2262.04   389.6 2264.36
   399.4 2264.72   448.6 2264.85   458.4 2265.19   468.2 2266.41   478.1  2268.7
   497.7 2274.14   507.6 2276.52   517.4  2278.5   527.2 2280.07     537 2281.18
#Mann= 3 , 0 , 0
       0      .1       0   320.8    .045       0  349.86      .1       0
#XS Ineff= 2 , 0
          243.38 2261.57
Permanent Ineff=
       F       F
Bank Sta=320.8,349.86
XS Rating Curve= 0 ,0
Exp/Cntr=0.3,0.1

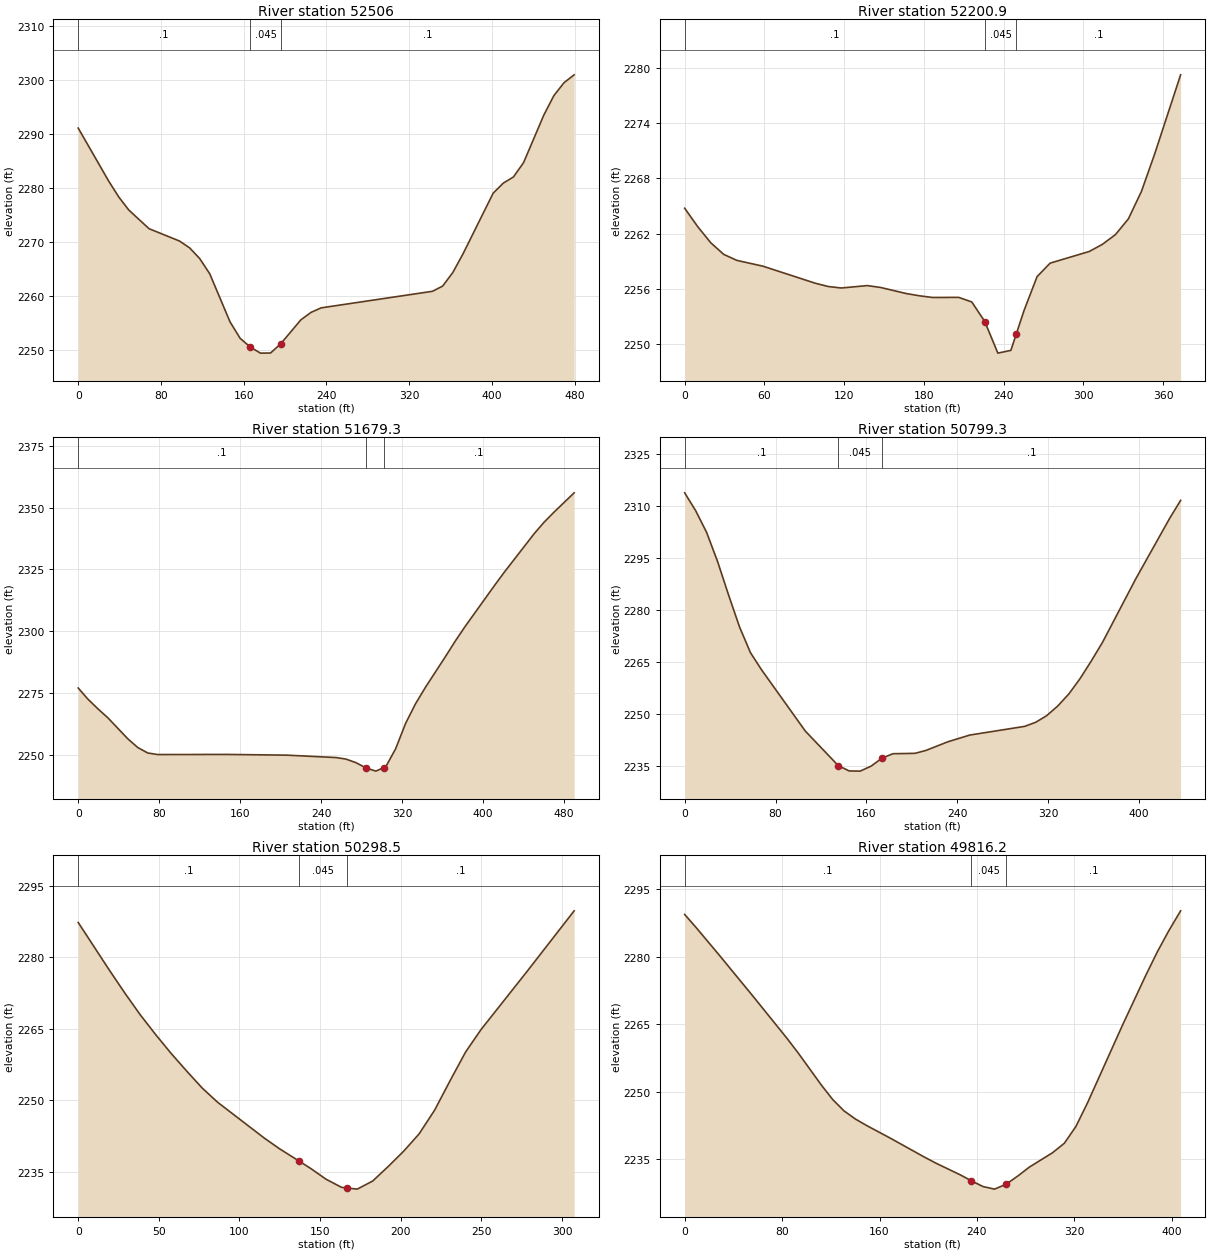
Type RM Length L Ch R = 1 ,52506   ,314.5,305.1,295.6
XS GIS Cut Line= 2
     1959875.357      389866.177     1960354.523       389887.01
#Sta/Elev= 30
       0 2291.13    29.4 2281.34    39.2 2278.38    48.9 2275.96    68.5  2272.5
    97.9 2270.22   107.7 2268.96   117.5 2266.97   127.2 2264.15   146.8 2255.26
   156.6  2252.2   166.4 2250.59   176.2 2249.46     186 2249.48   195.8 2251.18
   215.3 2255.62   225.1    2257   234.9 2257.84   342.6 2260.91   352.4 2261.87
   362.2 2264.37     372 2267.79   401.3 2279.08   411.1 2280.94   420.9 2282.08
   430.7 2284.74   450.2 2293.51     460 2297.14   469.8 2299.53   479.6 2300.99
#Mann= 3 , 0 , 0
       0      .1       0   166.4    .045       0   195.8      .1       0
Bank Sta=166.4,195.8
XS Rating Curve= 0 ,0
Exp/Cntr=0.3,0.1

Type RM Length L Ch R = 1 ,52200.9 ,508.7,521.6,534.4
XS GIS Cut Line= 2
      1959918.76      390231.628      1960271.19      390109.232
#Sta/Elev= 30
       0 2264.75     9.8 2262.75    19.6    2261    29.4 2259.73    39.3 2259.08
    58.9 2258.45    98.2  2256.6     108 2256.24   117.8 2256.08   137.4 2256.34
   147.3 2256.14   166.9 2255.47   176.7 2255.23   186.5 2255.05   206.2 2255.06
     216 2254.56   225.8 2252.43   235.6    2249   245.4  2249.3   249.4 2251.05
   255.3 2253.63   265.1 2257.31   274.9 2258.78   304.4 2260.05   314.2 2260.82
     324 2261.87   333.8 2263.59   343.6 2266.57   353.4 2270.57   373.1 2279.25
#Mann= 3 , 0 , 0
       0      .1       0   225.8    .045       0   249.4      .1       0
Bank Sta=225.8,249.4
XS Rating Curve= 0 ,0
Exp/Cntr=0.3,0.1

Type RM Length L Ch R = 1 ,51679.3 ,879.2,880,880.5
XS GIS Cut Line= 2
     1959875.357      390588.399     1960351.051      390706.455
#Sta/Elev= 30
       0    2277     9.8  2272.4    19.6 2268.53    29.4  2264.9      49 2256.45
    58.8 2252.93    68.6 2250.72    78.4 2250.07     147 2250.11   205.8 2249.83
   254.9 2248.85   264.7 2248.22   274.5 2246.78   284.3 2244.68   294.1 2243.36
   301.9 2244.74   303.9  2245.1   313.7 2252.41   323.5 2262.64   333.3 2270.59
   343.1 2277.25   362.7 2289.57   372.5 2295.91   382.3 2301.86   411.7 2318.66
   421.5 2324.09   450.9  2339.6   460.7 2344.22   470.5 2348.28   490.1 2355.98
#Mann= 3 , 0 , 0
       0      .1       0   284.3    .045       0   301.9      .1       0
Bank Sta=284.3,301.9
XS Rating Curve= 0 ,0
Exp/Cntr=0.3,0.1

Type RM Length L Ch R = 1 ,50799.3 ,492.1,500.8,509.7
XS GIS Cut Line= 3
     1959455.218       391262.01     1959760.773      391352.288
     1959840.635      391439.093
#Sta/Elev= 30
       0  2313.9     9.6 2308.79    19.3 2302.49      29 2294.03    38.6 2284.43
    48.3 2275.15    57.9 2267.74    67.6 2262.81   106.2 2245.07   135.2  2235.1
   144.8 2233.55   154.5  2233.5   164.1 2234.94   173.8 2237.26   183.4 2238.53
   202.8 2238.64   212.4 2239.48   231.7 2241.98     251 2243.92   299.3 2246.43
     309 2247.61   318.6  2249.5   328.4  2252.3   338.3 2255.83   348.1 2260.24
   357.9 2265.29   367.8 2270.68   397.2  2289.1   426.7 2306.38   436.6 2311.72
#Mann= 3 , 0 , 0
       0      .1       0   135.2    .045       0   173.8      .1       0
Bank Sta=135.2,173.8
XS Rating Curve= 0 ,0
Exp/Cntr=0.3,0.1

Type RM Length L Ch R = 1 ,50298.5 ,480.9,482.3,483.7
XS GIS Cut Line= 2
     1959262.116      391640.547       1959501.7      391833.256
#Sta/Elev= 27
       0 2287.27    19.2 2277.34    28.8 2272.53    38.4 2267.95      48 2263.78
    57.6 2259.83    67.3 2256.11    76.9 2252.56    86.5 2249.57   115.3  2242.1
   124.9 2239.82     1372237.251   144.1 2235.72   153.7 2233.45   163.3 2231.75
   166.42231.634     173 2231.38   182.6 2233.08   192.2 2236.12   201.8 2239.33
   211.4 2242.97     221 2247.94   230.6 2254.12   240.2 2260.12   249.8 2264.84
   278.6 2277.14   307.5 2289.71
#Mann= 3 , 0 , 0
       0      .1       0     137    .045       0   166.4      .1       0
Bank Sta=137,166.4
XS Rating Curve= 0 ,0
Exp/Cntr=0.3,0.1

Type RM Length L Ch R = 1 ,49816.2 ,654.4,657.2,659.7
XS GIS Cut Line= 3
     1958930.912      391914.788     1959014.246      392050.205
     1959198.273      392216.871
#Sta/Elev= 30
       0 2289.37     9.4 2286.46    28.1 2280.44    56.1 2271.23    84.2 2261.82
    93.5 2258.53   112.2 2251.53   121.6 2248.29   130.9 2245.77   140.3 2243.96
   149.6 2242.51   168.6 2239.77   197.2 2235.48   206.8 2234.12   225.8 2231.66
   235.4 2230.28     245 2228.99   254.5 2228.42     264 2229.51   273.6 2231.33
   283.1 2233.31   302.2 2236.51   311.8  2238.6   321.3 2242.32   330.9 2247.59
   359.5 2264.76   378.6  2275.8   388.2 2281.08   397.7  2285.8   407.3 2290.17
#Mann= 3 , 0 , 0
       0      .1       0   235.4    .045       0     264      .1       0
Bank Sta=235.4,264
XS Rating Curve= 0 ,0
Exp/Cntr=0.3,0.1

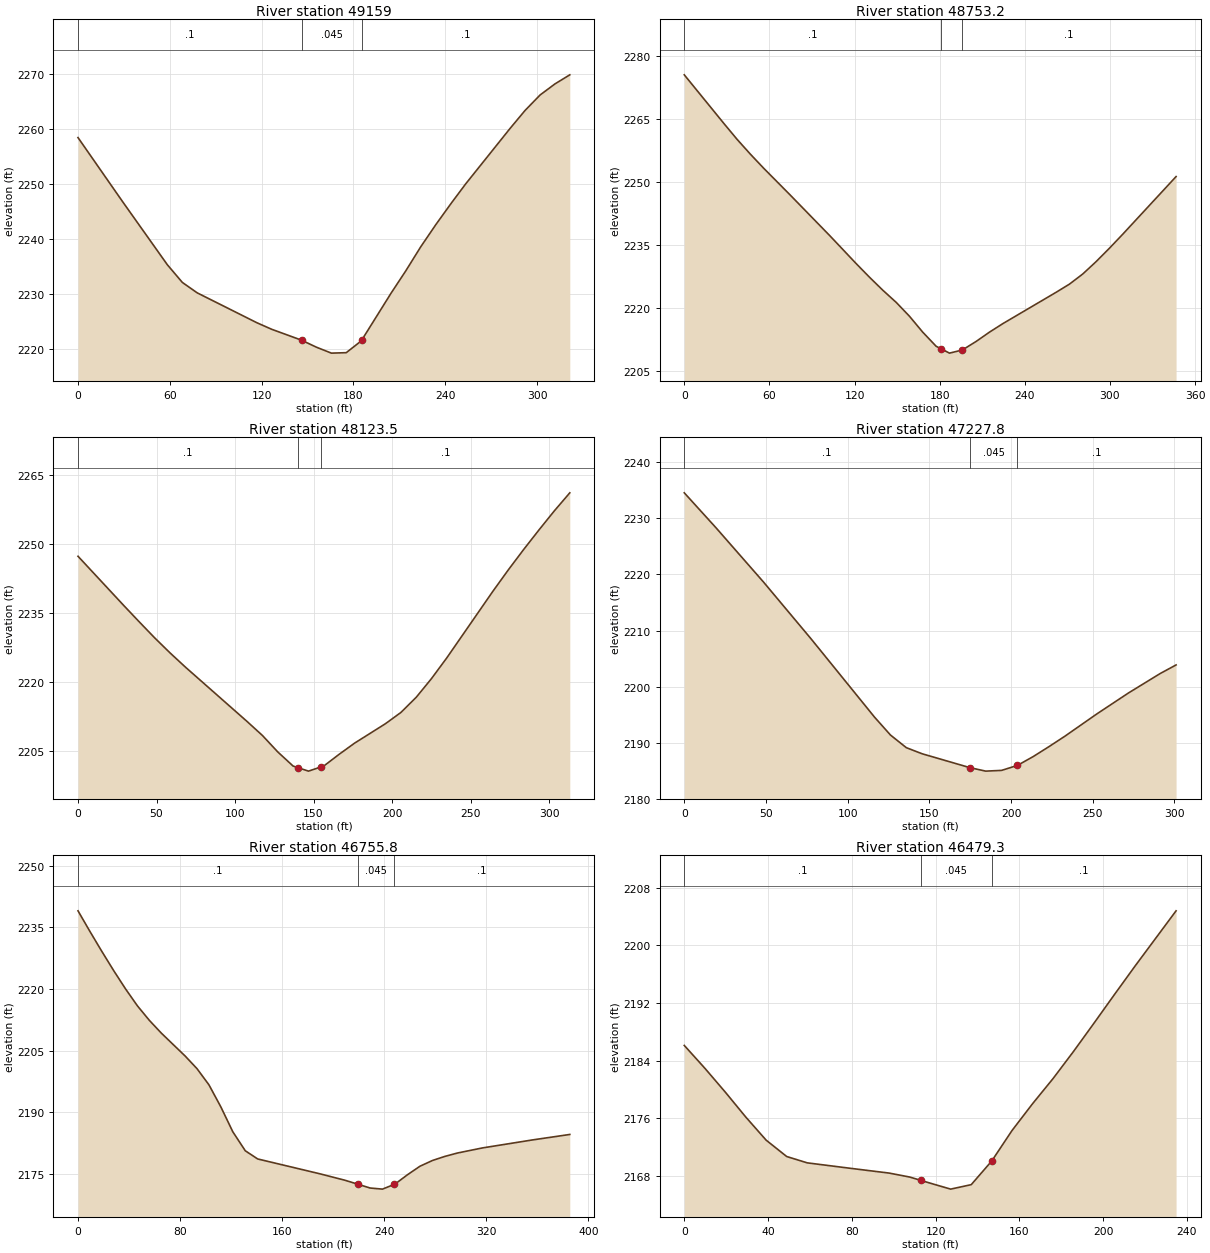
Type RM Length L Ch R = 1 ,49159   ,415.1,405.8,396.4
XS GIS Cut Line= 2
     1958465.241      392328.047     1958673.575      392572.839
#Sta/Elev= 24
       0 2258.41    29.2 2246.75    58.4 2235.31    68.2  2232.1    77.9 2230.21
   116.9 2224.78   126.6 2223.59   146.1 2221.61   155.8 2220.34   165.6 2219.26
   175.3 2219.34   185.1 2221.48  185.35 2221.59   204.6 2230.15   214.3 2234.24
     224 2238.58   233.8 2242.58   243.5 2246.33   253.3 2249.98   282.5 2260.12
   292.2 2263.35     302 2266.15   311.7 2268.16   321.4 2269.81
#Mann= 3 , 0 , 0
       0      .1       0   146.1    .045       0  185.35      .1       0
Bank Sta=146.1,185.35
XS Rating Curve= 0 ,0
Exp/Cntr=0.3,0.1

Type RM Length L Ch R = 1 ,48753.2 ,618.5,629.7,640.6
XS GIS Cut Line= 3
     1958156.607      392650.899     1958278.135      392737.705
     1958455.218       392824.51
#Sta/Elev= 27
       0 2275.43      28 2263.83    37.3 2260.06    46.7 2256.53      56 2253.21
    74.7 2246.84   102.7 2237.14   121.3  2230.5   130.7 2227.26     140  2224.2
   149.4 2221.32   158.7 2218.04   168.1 2214.24   177.5  2210.9     181 2210.29
   186.9 2209.27     196 2210.02   205.7 2212.05   215.1 2214.26   224.5 2216.28
     262 2223.72   271.4 2225.66   280.8 2228.07   290.2 2231.01   299.6  2234.2
     309 2237.53   346.6 2251.24
#Mann= 3 , 0 , 0
       0      .1       0     181    .045       0     196      .1       0
Bank Sta=181,196
XS Rating Curve= 0 ,0
Exp/Cntr=0.3,0.1

Type RM Length L Ch R = 1 ,48123.5 ,897.2,895.7,894.2
XS GIS Cut Line= 2
     1957774.662      393060.621      1957958.69      393314.093
#Sta/Elev= 27
       0 2247.32    29.4  2236.5    39.2 2232.96    48.9 2229.52    58.7 2226.24
    68.5 2223.14   107.7 2211.32   117.5 2208.26   127.2  2204.7     137 2201.61
   139.82201.296   146.8 2200.51   154.82201.432   156.6 2201.64   166.4  2204.2
   176.2 2206.62   195.8 2210.84   205.6 2213.28   215.4  2216.6   225.1 2220.66
   234.9  2225.2   264.3 2239.73   274.1 2244.38   283.9 2248.83   293.7 2253.11
   303.4 2257.23   313.2 2261.14
#Mann= 3 , 0 , 0
       0      .1       0   139.8    .045       0   154.8      .1       0
Bank Sta=139.8,154.8
XS Rating Curve= 0 ,0
Exp/Cntr=0.3,0.1

Type RM Length L Ch R = 1 ,47227.8 ,491.2,472,452.8
XS GIS Cut Line= 2
     1957010.773      393536.316     1957201.746      393768.955
#Sta/Elev= 19
       0 2234.53    19.4 2228.31    48.6  2218.6    77.7 2208.48   116.5 2194.55
   126.2 2191.38   135.9 2189.13   145.6 2188.04   174.8 2185.57   184.5 2184.95
   194.2 2185.08   203.9 2185.97   213.6 2187.55   223.3 2189.33     233 2191.18
   252.4 2195.12   271.9 2198.88   291.3 2202.34     301 2203.87
#Mann= 3 , 0 , 0
       0      .1       0   174.8    .045       0   203.9      .1       0
Bank Sta=174.8,203.9
XS Rating Curve= 0 ,0
Exp/Cntr=0.3,0.1

Type RM Length L Ch R = 1 ,46755.8 ,260.5,276.5,291.2
XS GIS Cut Line= 3
     1956611.468      393973.816     1956722.579      394022.427
     1956986.468      394032.843
#Sta/Elev= 30
       0 2239.05     9.3 2234.06    18.7 2229.17      28 2224.49    37.3 2220.04
    46.6 2215.92      56 2212.38    65.3  2209.3      84 2203.72    93.3 2200.64
   102.6 2196.73     112 2191.32   121.3 2185.31   131.1 2180.68   140.8 2178.69
   189.8 2175.06   209.3  2173.5   219.1 2172.57   228.9 2171.62   238.6 2171.35
   247.8  2172.5   248.4 2172.57   258.2 2174.85     268 2176.92   277.8 2178.32
   287.6 2179.32   297.3 2180.13   316.9 2181.37     356 2183.31   385.4 2184.65
#Mann= 3 , 0 , 0
       0      .1       0   219.1    .045       0   247.8      .1       0
Bank Sta=219.1,247.8
XS Rating Curve= 0 ,0
Exp/Cntr=0.3,0.1

Type RM Length L Ch R = 1 ,46479.3 ,220.3,228.4,236
XS GIS Cut Line= 2
     1956746.885      394216.871     1956930.912      394362.705
#Sta/Elev= 27
       0 2186.11     9.8 2182.95    19.6 2179.62    29.4 2176.15    39.1 2172.95
    48.9 2170.68    58.7  2169.8    68.5 2169.44    78.3 2169.08      88 2168.73
    97.8 2168.38   107.6 2167.83   112.8 2167.38   117.4 2166.98   127.2 2166.15
   127.8 2166.19     137 2166.77   146.8 2170.06   156.5  2174.3   166.3 2178.02
   176.1 2181.52   185.9  2185.3   195.7 2189.24   205.4 2193.19   215.2 2197.13
     225 2200.97   234.8 2204.81
#Mann= 3 , 0 , 0
       0      .1       0   112.8    .045       0   146.8      .1       0
Bank Sta=112.8,146.8
XS Rating Curve= 0 ,0
Exp/Cntr=0.3,0.1

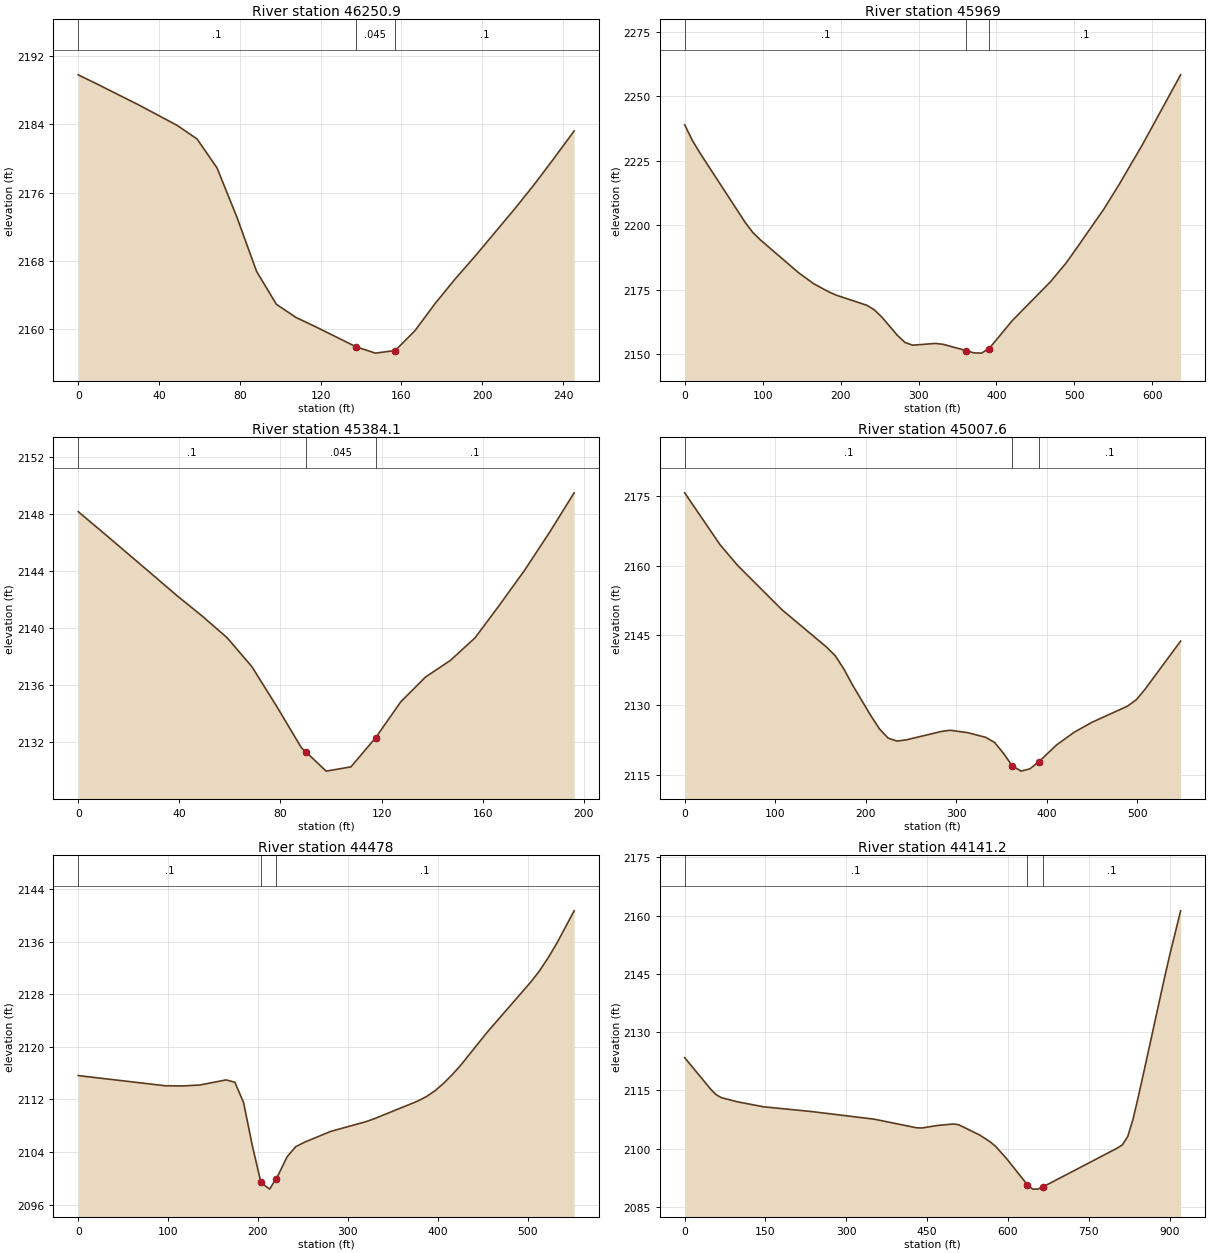
Type RM Length L Ch R = 1 ,46250.9 ,300.1,281.9,264.1
XS GIS Cut Line= 3
     1956587.162      394303.677     1956673.968      394446.038
     1956726.051      394505.066
#Sta/Elev= 28
       0  2189.8     9.8 2188.67    19.6  2187.5    29.4 2186.34    39.2 2185.11
      49 2183.87    58.8 2182.29    68.7  2178.9    78.5 2173.15    88.3 2166.76
    98.1  2162.9   107.9 2161.35   117.7 2160.25   127.5  2159.1   137.3 2157.95
   139.8 2157.75   147.1 2157.18   154.8 2157.42   156.9 2157.48   166.7 2159.81
   176.6 2162.97   186.4 2165.82   196.3  2168.5   206.1 2171.27   215.9 2174.04
   225.8 2176.96   235.6 2180.04   245.5 2183.22
#Mann= 3 , 0 , 0
       0      .1       0   137.3    .045       0   156.9      .1       0
Bank Sta=137.3,156.9
XS Rating Curve= 0 ,0
Exp/Cntr=0.3,0.1

Type RM Length L Ch R = 1 ,45969   ,596.2,584.9,572.9
XS GIS Cut Line= 3
     1956218.239      394481.628     1956436.989      394627.461
     1956798.968      394718.607
#Sta/Elev= 30
       0 2238.96     9.7 2232.98    19.5 2228.06    77.9 2200.98    87.6 2197.14
    97.4 2194.26   146.1 2181.61   165.5 2177.34     185 2174.16   194.7 2172.87
   233.7 2168.98   243.4 2167.19   253.2 2164.32   272.7 2157.38   282.6 2154.57
   292.4 2153.51   321.8 2154.19   331.7 2153.83   361.1 2151.42     371 2150.53
   380.8 2150.43   390.6 2152.22   420.1 2162.98   469.2 2178.09   488.8 2185.19
   498.7 2189.34     538 2206.39   557.6 2215.95   587.1 2231.18   636.2 2258.32
#Mann= 3 , 0 , 0
       0      .1       0   361.1    .045       0   390.6      .1       0
Bank Sta=361.1,390.6
XS Rating Curve= 0 ,0
Exp/Cntr=0.3,0.1

Type RM Length L Ch R = 1 ,45384.1 ,366.3,376.5,386.5
XS GIS Cut Line= 2
      1956208.69      395046.732     1956399.662      395001.593
#Sta/Elev= 23
       0 2148.16     9.8  2146.7    19.6 2145.22    29.4 2143.74    39.2 2142.25
    49.1 2140.83    58.9 2139.32    68.7 2137.29    78.5 2134.51    88.3  2131.6
      90 2131.32    98.1 2129.96     105 2130.17   107.9 2130.26   117.7 2132.31
   127.6 2134.82   137.4 2136.56   147.2 2137.72     157 2139.31   166.8 2141.64
   176.6 2144.05   186.4 2146.69   196.2 2149.48
#Mann= 3 , 0 , 0
       0      .1       0      90    .045       0   117.7      .1       0
Bank Sta=90,117.7
XS Rating Curve= 0 ,0
Exp/Cntr=0.3,0.1

Type RM Length L Ch R = 1 ,45007.6 ,540.5,529.7,518.6
XS GIS Cut Line= 3
     1955923.968      395251.593     1956080.218      395352.288
     1956434.385      395428.677
#Sta/Elev= 30
       0 2175.69    39.1 2164.52    58.7 2160.02   107.6 2150.51   156.5 2142.53
   166.3 2140.65   176.1 2137.72   185.9 2134.19   205.5  2127.8   215.3 2124.86
     225 2122.86   234.8 2122.24   244.6 2122.49   283.8 2124.31   293.6 2124.57
   313.2 2124.04   332.8 2123.04   342.6 2121.94   352.4 2119.61   362.1  2116.9
   371.9 2115.77   381.7 2116.27   391.5 2117.79   411.1 2121.41   430.7 2124.16
   450.3 2126.29   489.4 2129.75   499.2 2131.14     509 2133.43   548.2 2143.77
#Mann= 3 , 0 , 0
       0      .1       0   362.1    .045       0   391.5      .1       0
Bank Sta=362.1,391.5
XS Rating Curve= 0 ,0
Exp/Cntr=0.3,0.1

Type RM Length L Ch R = 1 ,44478   ,333.4,336.8,340.3
XS GIS Cut Line= 2
     1956038.551      395959.927     1956570.669      395813.659
#Sta/Elev= 30
       0 2115.64    96.8 2114.09   116.2 2114.06   135.5 2114.21   164.6 2114.98
   174.3 2114.62     184 2111.53   193.6 2105.06   203.3 2099.37     213 2098.36
   220.1 2099.96   222.7 2100.55   232.4 2103.28     242 2104.82   251.7 2105.49
   280.8 2107.14   319.5  2108.6   329.2 2109.06   377.6 2111.75   387.3 2112.43
     397 2113.33   406.6 2114.47   416.3  2115.8     426 2117.28     455 2122.23
   503.4 2129.85   513.1 2131.55   522.8 2133.54   532.5 2135.77   551.8 2140.71
#Mann= 3 , 0 , 0
       0      .1       0   203.3    .045       0   220.1      .1       0
Bank Sta=203.3,220.1
XS Rating Curve= 0 ,0
Exp/Cntr=0.3,0.1

Type RM Length L Ch R = 1 ,44141.2 ,318,335.9,352.7
XS GIS Cut Line= 3
      1955763.51      396074.375     1956109.864      396233.229
     1956646.322      396175.937
#Sta/Elev= 30
       0 2123.41    48.8 2115.21    58.6 2113.85    68.4 2113.09    97.7 2112.04
   146.6 2110.74   234.5 2109.54   351.7 2107.56   430.1 2105.35   439.9 2105.28
   469.3 2105.93   498.8 2106.32   508.6 2106.13   547.8 2103.46   567.4 2101.69
   577.2 2100.54   596.8 2097.53   636.1 2090.67   645.9 2089.53   655.7 2089.54
   665.5 2090.14   802.8 2100.08   812.6 2100.95   822.5  2103.1   832.3 2107.56
   842.1 2113.37   851.9 2119.46   891.1 2144.26   900.9 2150.14   920.6 2161.25
#Mann= 3 , 0 , 0
       0      .1       0   636.1    .045       0   665.5      .1       0
Bank Sta=636.1,665.5
XS Rating Curve= 0 ,0
Exp/Cntr=0.3,0.1