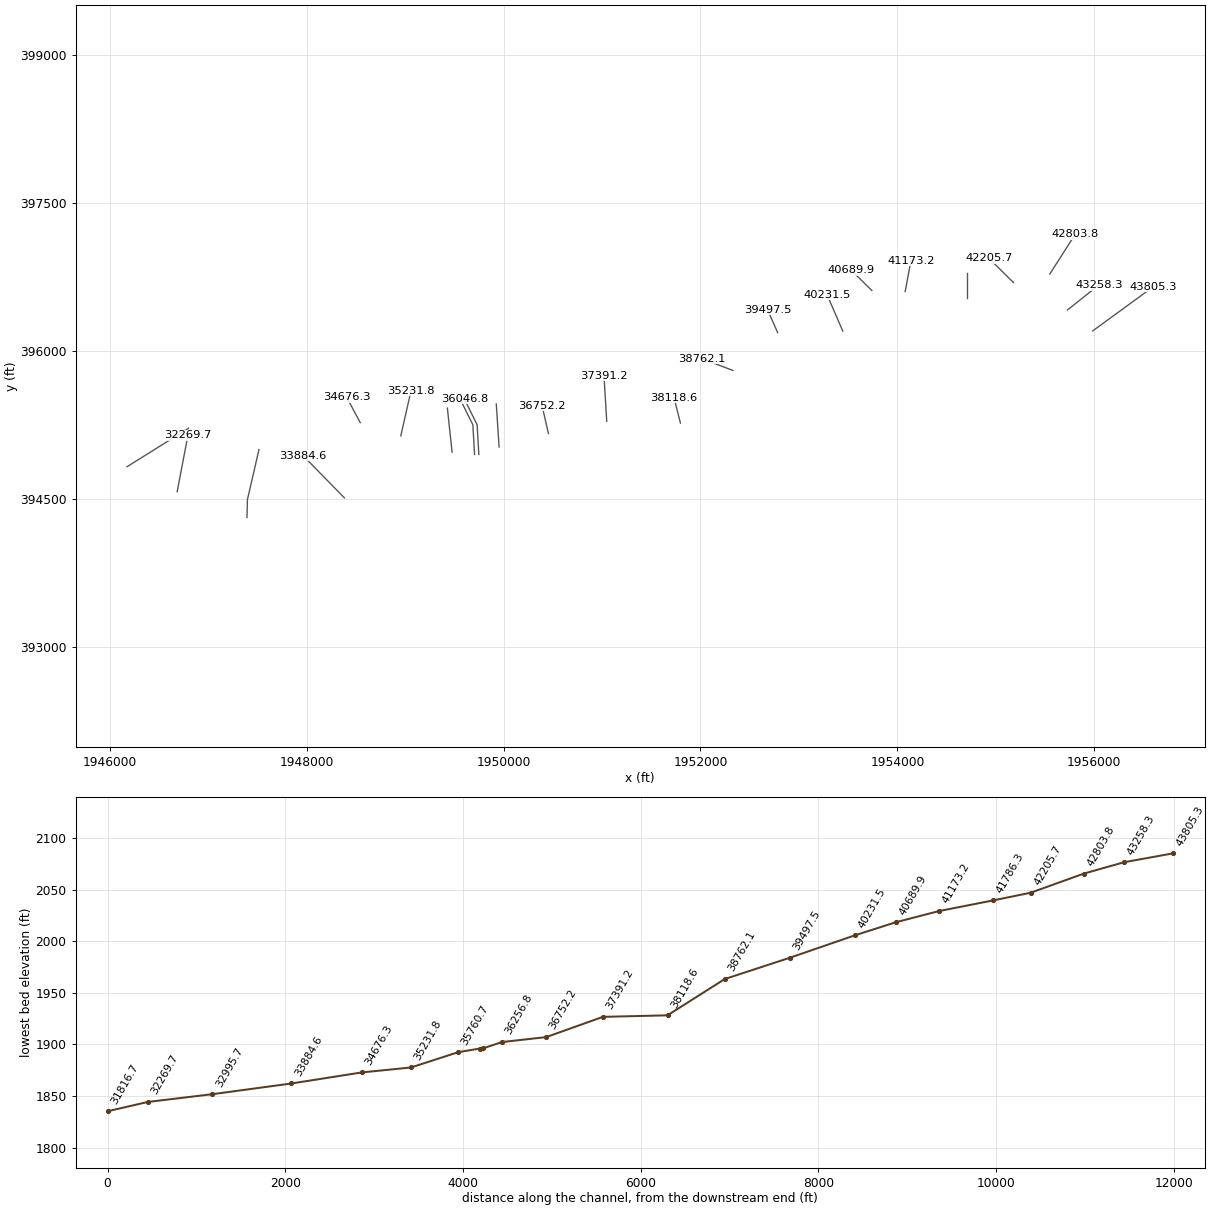
HEC-RAS study MUDDYCK2.prj: MUDDYCK2

--- MUDDYCK2.g01 (geometry) --- (continued)

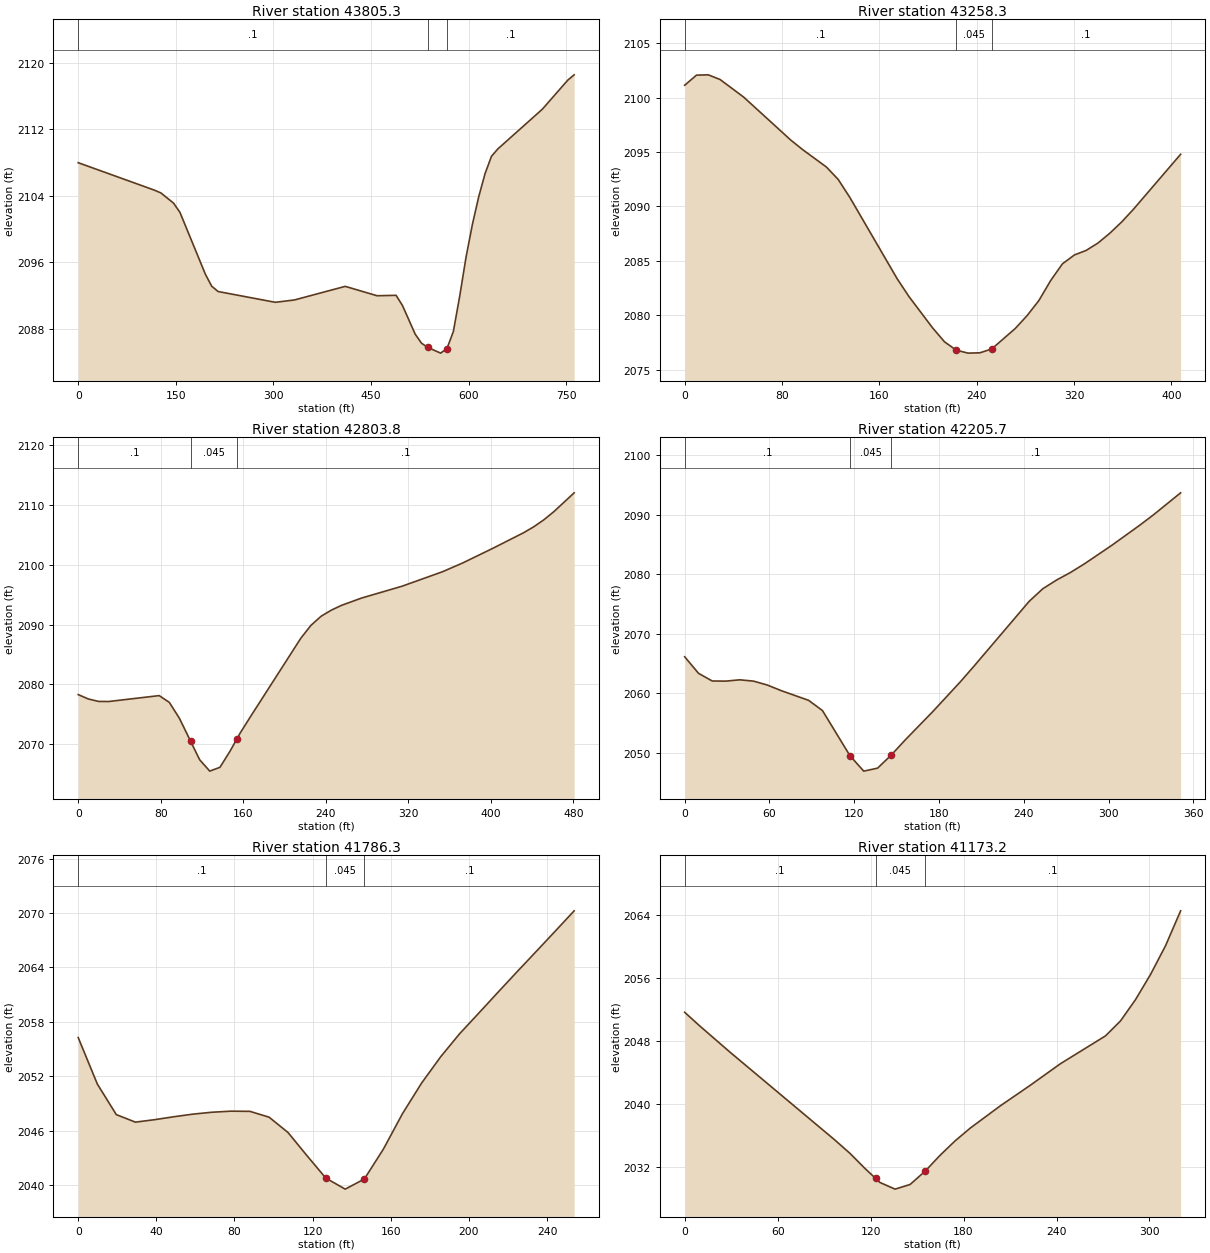
Type RM Length L Ch R = 1 ,43805.3 ,549.1,547,542.9
XS GIS Cut Line= 2
     1955984.864      396204.583     1956601.051      396653.503
#Sta/Elev= 30
       0 2107.97   117.3 2104.66   127.1 2104.33   146.6  2103.1   156.4 2101.99
   195.5 2094.54   205.2  2093.1     215 2092.46     303 2091.16   332.3 2091.44
   410.5 2093.08   459.4 2091.95   488.7    2092   498.5 2090.77     518 2087.33
   527.8 2086.23   537.6 2085.72   557.1 2085.04   566.9 2085.59   576.7 2087.64
   586.4 2091.86   596.2 2096.59     606 2100.55   615.8  2103.9   625.5 2106.67
   635.3 2108.74   645.1 2109.63   713.5 2114.41   752.6 2117.91   762.4 2118.55
#Mann= 3 , 0 , 0
       0      .1       0   537.6    .045       0   566.9      .1       0
Bank Sta=537.6,566.9
XS Rating Curve= 0 ,0
Exp/Cntr=0.3,0.1

Type RM Length L Ch R = 1 ,43258.3 ,442.7,454.4,466
XS GIS Cut Line= 2
     1955728.655      396416.958     1956047.666      396670.864
#Sta/Elev= 30
       0 2101.15     9.7 2102.08    19.4 2102.11    29.1 2101.68    48.5 2100.06
    87.4 2096.09    97.1 2095.22   116.5 2093.63   126.2 2092.49   135.9 2090.81
   174.7 2083.35   184.4 2081.71   203.9 2078.82   213.6 2077.55   223.3 2076.78
     233 2076.51   242.7 2076.54   252.4 2076.89   271.8 2078.78   281.5 2079.96
   291.2 2081.35   300.9 2083.19   310.6 2084.73   320.4 2085.54   330.1 2085.96
   339.8 2086.64   349.5 2087.54   359.2 2088.57   368.9 2089.74   407.7  2094.8
#Mann= 3 , 0 , 0
       0      .1       0   223.3    .045       0   252.4      .1       0
Bank Sta=223.3,252.4
XS Rating Curve= 0 ,0
Exp/Cntr=0.3,0.1

Type RM Length L Ch R = 1 ,42803.8 ,567.2,598.2,629
XS GIS Cut Line= 2
     1955548.534      396781.541      1955807.78      397186.354
#Sta/Elev= 30
       0 2078.28     9.8 2077.55    19.6 2077.14    29.4 2077.12    78.5 2078.11
    88.3 2076.98    98.1 2074.31     1092070.452   117.7 2067.38   127.5 2065.47
   137.4 2066.11   147.2 2068.82   153.7 2070.83     157 2071.85   166.8 2074.54
   215.8 2087.72   225.6 2089.87   235.4 2091.39   245.3 2092.41   255.1 2093.21
   274.7 2094.44   313.9 2096.42   353.2 2098.85   372.8 2100.32   402.2 2102.79
   431.7 2105.37   441.5 2106.36   451.3 2107.53   461.1 2108.91   480.7 2112.05
#Mann= 3 , 0 , 0
       0      .1       0     109    .045       0   153.7      .1       0
Bank Sta=109,153.7
XS Rating Curve= 0 ,0
Exp/Cntr=0.3,0.1

Type RM Length L Ch R = 1 ,42205.7 ,437.3,419.4,401.5
XS GIS Cut Line= 2
      1955179.61      396694.736     1954930.176      396941.562
#Sta/Elev= 27
       0 2066.14     9.8 2063.36    19.5 2062.07    29.2 2062.05      39 2062.27
    48.7 2062.05    58.5 2061.39    68.2 2060.46    87.7 2058.82    97.5  2057.1
     117  2049.5   126.7 2046.93   136.5 2047.43   146.2 2049.64     156 2052.16
   175.5 2056.92     195 2061.92   204.7 2064.56   243.7 2075.44   253.4 2077.57
   263.2 2079.04   272.9 2080.29   282.7 2081.73   302.2 2084.86   321.7 2088.19
   331.4 2089.93   350.9 2093.68
#Mann= 3 , 0 , 0
       0      .1       0     117    .045       0   146.2      .1       0
Bank Sta=117,146.2
XS Rating Curve= 0 ,0
Exp/Cntr=0.3,0.1

Type RM Length L Ch R = 1 ,41786.3 ,617,613.1,609.1
XS GIS Cut Line= 2
      1954706.52      396536.316      1954706.52      396790.222
#Sta/Elev= 28
       0 2056.26     9.8 2051.13    19.5 2047.76    29.3 2046.93    39.1  2047.2
    48.8 2047.52    58.6 2047.81    68.4 2048.02    78.1 2048.14    87.9 2048.12
    97.7 2047.48   107.4 2045.79   117.2 2043.21   126.8 2040.75   136.7 2039.54
   141.8 2040.12   146.5 2040.66   156.2 2043.94     166 2047.86   175.8 2051.24
   185.6 2054.15   195.3 2056.69   205.1 2058.96   214.8 2061.23   224.6  2063.5
   234.4 2065.74   244.1 2067.97   253.9 2070.24
#Mann= 3 , 0 , 0
       0      .1       0   126.8    .045       0   146.5      .1       0
Bank Sta=126.8,146.5
XS Rating Curve= 0 ,0
Exp/Cntr=0.3,0.1

Type RM Length L Ch R = 1 ,41173.2 ,461.1,483.3,505.5
XS GIS Cut Line= 2
      1954079.35       396603.59     1954137.944       396918.26
#Sta/Elev= 23
       0 2051.61     9.7 2049.88    29.1 2046.57      97 2035.37   106.7 2033.68
   116.4 2031.76   123.2 2030.51   126.1 2029.98   135.8 2029.14   145.5 2029.73
   155.2 2031.42   164.9 2033.45   174.6 2035.28   184.3 2036.89   203.7 2039.72
   223.1 2042.34   242.5 2045.07   271.6 2048.61   281.3 2050.51     291 2053.22
   300.7 2056.42   310.4 2060.08   320.1  2064.5
#Mann= 3 , 0 , 0
       0      .1       0   123.2    .045       0   155.2      .1       0
Bank Sta=123.2,155.2
XS Rating Curve= 0 ,0
Exp/Cntr=0.3,0.1

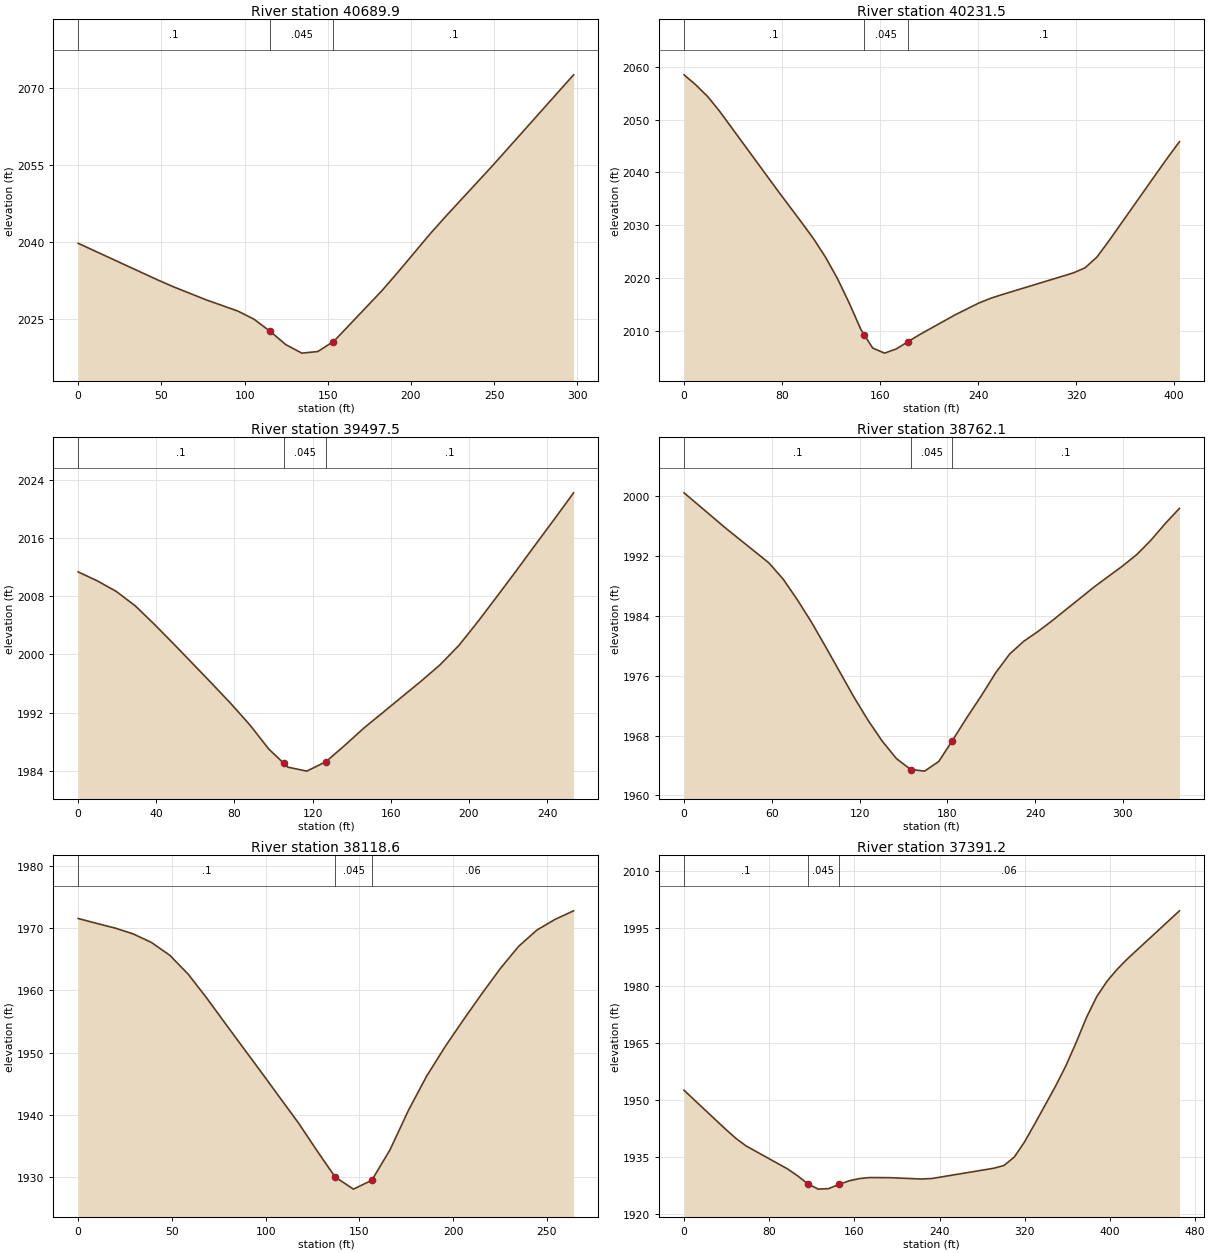
Type RM Length L Ch R = 1 ,40689.9 ,467,458.4,449.7
XS GIS Cut Line= 2
     1953740.808      396614.441     1953528.135      396822.774
#Sta/Elev= 18
       0 2039.74      48 2032.58    57.6 2031.23    76.8 2028.75      96 2026.54
   105.6 2024.98   115.2 2022.64   124.8 2020.01   134.4 2018.36     144 2018.67
   153.22020.576   153.7 2020.68   182.5 2030.51   192.1 2034.09   211.3 2041.51
   220.9 2044.99   249.7  2055.1   297.7 2072.54
#Mann= 3 , 0 , 0
       0      .1       0   115.2    .045       0   153.2      .1       0
Bank Sta=115.2,153.2
XS Rating Curve= 0 ,0
Exp/Cntr=0.3,0.1

Type RM Length L Ch R = 1 ,40231.5 ,731.4,734,735.8
XS GIS Cut Line= 2
     1953445.669      396202.114     1953285.079      396573.208
#Sta/Elev= 28
       0 2058.46     9.6 2056.56    19.2 2054.37    28.9 2051.61      77 2036.38
    96.3 2030.42   105.9 2027.37   115.5 2023.94   125.2 2019.91   134.8 2015.28
   144.4 2010.24   147.12009.256     154 2006.74   163.7 2005.78   173.3 2006.58
   182.9 2007.96   192.6 2009.32   221.4 2013.04   240.7 2015.27   250.3 2016.16
   259.9 2016.88   317.7 2020.96   327.3 2021.92     337 2023.95   346.6 2026.95
   385.1 2039.62   394.7 2042.75   404.4  2045.8
#Mann= 3 , 0 , 0
       0      .1       0   147.1    .045       0   182.9      .1       0
Bank Sta=147.1,182.9
XS Rating Curve= 0 ,0
Exp/Cntr=0.3,0.1

Type RM Length L Ch R = 1 ,39497.5 ,717.2,735.4,753.5
XS GIS Cut Line= 2
     1952783.777      396186.923      1952681.78      396419.128
#Sta/Elev= 29
       0 2011.35     9.8 2010.12    19.5 2008.67    29.3 2006.67      39 2004.15
    48.8 2001.48    58.5 1998.78    68.3 1996.05      78  1993.3    87.8 1990.35
    97.6    1987   105.2 1985.06   107.3 1984.52     117 1983.97   120.2 1984.39
   126.8 1985.26   136.6 1987.54   146.3  1989.9   156.1 1992.05   165.8 1994.19
   175.6 1996.35   185.3 1998.59   195.1 2001.31   204.8 2004.58   214.6 2008.05
   224.4 2011.56   234.1  2015.1   243.9 2018.65   253.6 2022.22
#Mann= 3 , 0 , 0
       0      .1       0   105.2    .045       0   126.8      .1       0
Bank Sta=105.2,126.8
XS Rating Curve= 0 ,0
Exp/Cntr=0.3,0.1

Type RM Length L Ch R = 1 ,38762.1 ,665.6,643.5,621.4
XS GIS Cut Line= 2
     1952330.218      395802.809     1952013.378      395922.166
#Sta/Elev= 29
       0 2000.47      29 1995.66      58  1991.1    67.7 1988.94    77.4 1986.18
    87.1 1983.17    96.7 1979.91   116.1 1973.16   125.8 1970.04   135.4 1967.28
   145.1 1964.94   154.8 1963.48   155.41963.465   164.4 1963.25   174.1 1964.54
   183.1 1967.24   193.5 1970.47   203.2 1973.33   212.8 1976.34   222.5  1978.9
   232.2 1980.62   241.8 1981.91   251.5 1983.35   280.5 1987.91   299.9 1990.71
   309.6 1992.24   319.2 1994.15   328.9 1996.36   338.6 1998.39
#Mann= 3 , 0 , 0
       0      .1       0   155.4    .045       0   183.1      .1       0
Bank Sta=155.4,183.1
XS Rating Curve= 0 ,0
Exp/Cntr=0.3,0.1

Type RM Length L Ch R = 1 ,38118.6 ,731.7,727.4,723
XS GIS Cut Line= 2
     1951796.364      395268.955      1951731.26      395525.031
#Sta/Elev= 30
       0 1971.53     9.8 1970.75    19.6    1970    29.4 1969.05    39.1 1967.68
    48.9 1965.62    58.7 1962.59    68.5 1958.79    78.3 1954.76    88.1 1950.76
    97.9 1946.78   107.6 1942.78   117.4 1938.77   127.2 1934.36     137 1930.08
   138.2 1929.84   146.8 1928.12   153.2 1929.05   156.6 1929.54   166.4 1934.48
   176.2  1940.8   185.9 1946.28   195.7 1950.97   205.5  1955.3   215.3 1959.47
   225.1 1963.49   234.9 1967.06   244.6 1969.67   254.4  1971.4   264.2 1972.76
#Mann= 3 , 0 , 0
       0      .1       0     137    .045       0   156.6     .06       0
Bank Sta=137,156.6
XS Rating Curve= 0 ,0
Exp/Cntr=0.3,0.1

Type RM Length L Ch R = 1 ,37391.2 ,634.8,639,643
XS GIS Cut Line= 2
     1951047.666      395286.316     1951019.454      395750.725
#Sta/Elev= 30
       0 1952.54    38.8 1942.39    48.5 1939.98    58.2 1937.96    96.9 1931.97
   106.6 1930.12   116.3    1928     126 1926.62   135.7 1926.75   145.4 1927.84
   155.1  1928.8   164.8 1929.39   174.5 1929.66   193.9 1929.62   222.9 1929.27
   232.6  1929.4   290.8 1932.09   300.5 1932.82   310.2 1935.04   319.9 1939.04
   329.6 1943.83     349 1953.65   358.6 1958.94   368.3 1965.07     378 1971.64
   387.7 1977.15   397.4 1981.18   407.1 1984.36   416.8  1987.1   465.3  1999.6
#Mann= 3 , 0 , 0
       0      .1       0   116.3    .045       0   145.4     .06       0
Bank Sta=116.3,145.4
XS Rating Curve= 0 ,0
Exp/Cntr=0.3,0.1

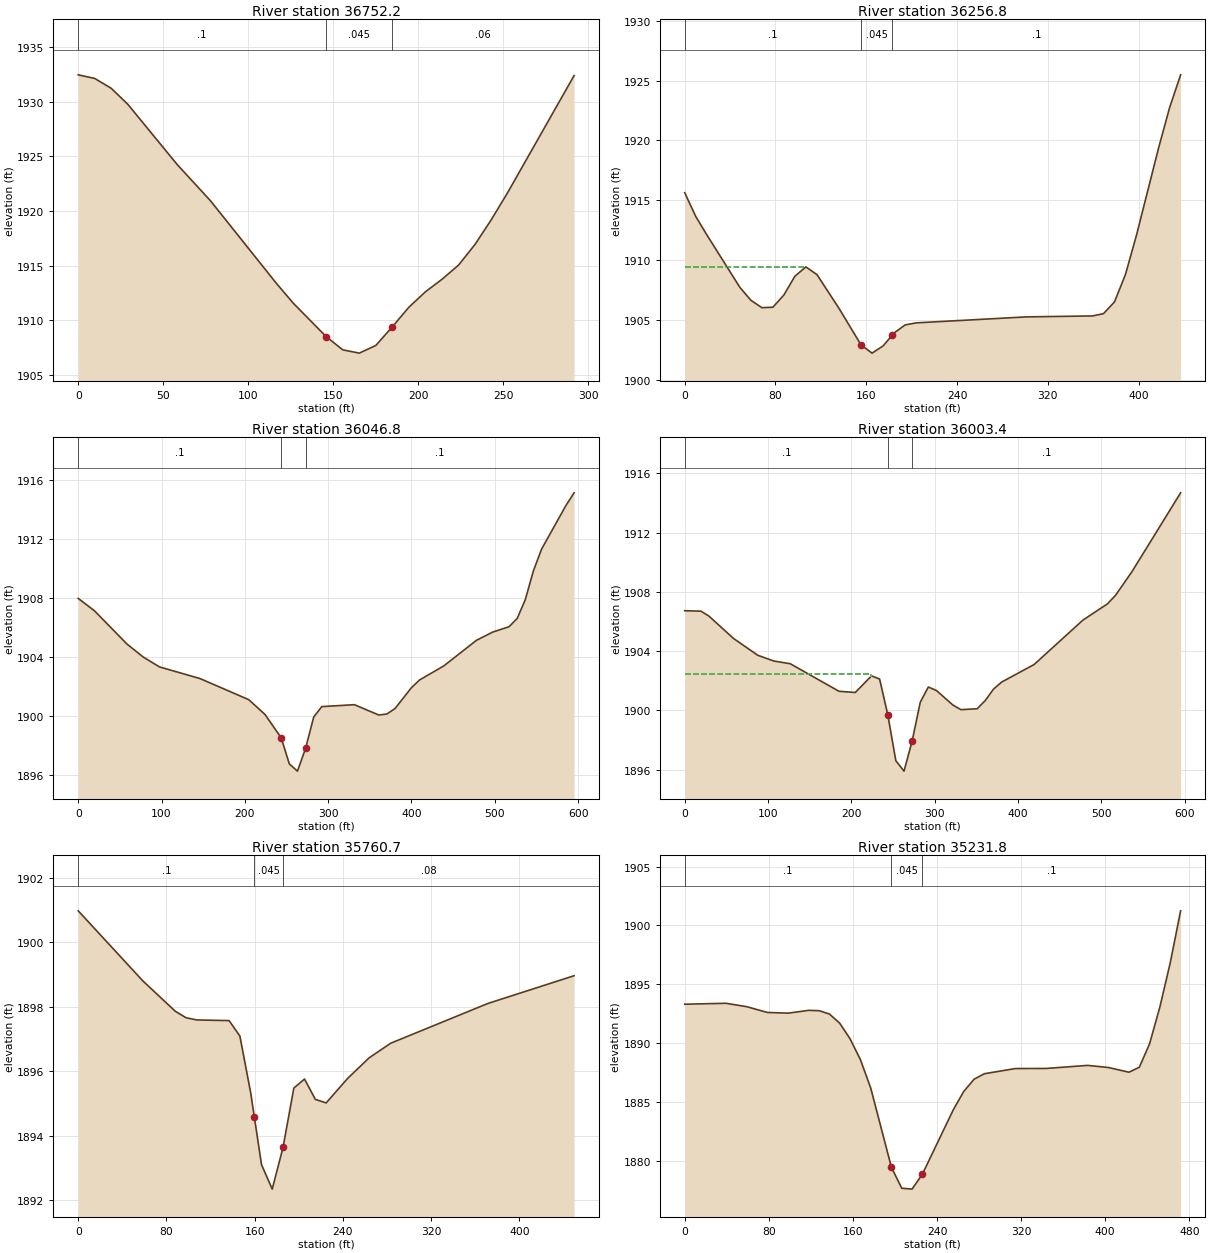
Type RM Length L Ch R = 1 ,36752.2 ,499.3,495.4,490.8
XS GIS Cut Line= 2
     1950455.218      395162.618     1950390.114      395446.906
#Sta/Elev= 21
       0 1932.44     9.7 1932.11    19.4 1931.21    29.2 1929.74    58.3 1924.22
    77.8 1920.92   116.7 1913.34   126.4 1911.57   145.8  1908.5   155.6 1907.29
   165.3 1906.99     175 1907.69   184.7 1909.39   194.4 1911.18   204.2  1912.6
   213.9 1913.74   223.6 1915.03   233.3 1916.92     243 1919.21   252.8 1921.74
   291.6 1932.37
#Mann= 3 , 0 , 0
       0      .1       0   145.8    .045       0   184.7     .06       0
Bank Sta=145.8,184.7
XS Rating Curve= 0 ,0
Exp/Cntr=0.3,0.1

Type RM Length L Ch R = 1 ,36256.8 ,210.1,210,210.7
XS GIS Cut Line= 2
     1949953.916      395025.899     1949925.704      395462.097
#Sta/Elev= 28
       0 1915.63     9.7 1913.65    19.4 1912.12    48.6 1907.72    58.3 1906.64
      68 1906.02    77.7 1906.06    87.4 1907.08    97.1 1908.65   106.8 1909.43
   116.6 1908.78     136 1905.96   155.4 1902.91   165.1 1902.22   174.8 1902.82
   183.1 1903.74   184.6 1903.91   194.3 1904.58     204 1904.75   301.1 1905.25
   359.4 1905.33   369.1 1905.52   378.8  1906.5   388.5  1908.8   398.3 1912.12
   417.7 1919.38   427.4 1922.75   437.1 1925.49
#Mann= 3 , 0 , 0
       0      .1       0   155.4    .045       0   183.1      .1       0
#XS Ineff= 2 , 0
          106.34 1909.42
Permanent Ineff=
       F       F
Bank Sta=155.4,183.1
XS Rating Curve= 0 ,0
Exp/Cntr=0.3,0.1

Type RM Length L Ch R = 1 ,36046.8 ,43.4,43.4,43.4
XS GIS Cut Line= 3
     1949748.295      394949.944     1949730.934      395251.593
     1949600.726       395514.18
#Sta/Elev= 30
       0 1907.96    19.5 1907.12    58.5 1904.87      78 1903.99    97.5 1903.32
   146.2 1902.53   204.7  1901.1   224.2  1900.1   243.7 1898.51   253.4 1896.75
   263.2 1896.26   272.9  1897.8   282.7 1899.93   292.4 1900.63   331.5 1900.76
   360.8 1900.06   370.5 1900.13   380.3  1900.5   399.8  1901.9   409.6 1902.43
   438.9 1903.39     478 1905.12   497.6 1905.68   517.1 1906.04   526.9  1906.6
   536.6 1907.87   546.4 1909.83   556.2  1911.3   585.5 1914.26   595.2 1915.11
#Mann= 3 , 0 , 0
       0      .1       0   243.7    .045       0   272.9      .1       0
Bank Sta=243.7,272.9
XS Rating Curve= 0 ,0
Exp/Cntr=0.3,0.1

Type RM Length L Ch R = 1 ,36003.4 ,241.6,242.7,243.8
XS GIS Cut Line= 3
     1949704.892      394949.944     1949687.531      395251.593
     1949557.323       395514.18
#Sta/Elev= 30
       0 1906.73    19.5  1906.7    29.2 1906.36    58.5 1904.86    87.7 1903.72
   107.2 1903.33   126.7 1903.15   185.2 1901.29   204.7 1901.21   224.2 1902.33
   233.9 1902.12   243.7 1899.71   253.4  1896.6   263.2  1895.9   272.9 1897.92
   282.7 1900.55   292.4 1901.58   302.2 1901.34   321.7 1900.37   331.5 1900.05
     351 1900.11   360.8 1900.67   370.5 1901.43   380.3 1901.91   419.4  1903.1
     478  1906.1   507.3 1907.19   517.1 1907.77   536.6 1909.35   595.2 1914.69
#Mann= 3 , 0 , 0
       0      .1       0   243.7    .045       0   272.9      .1       0
#XS Ineff= 2 , 0
           223.1 1902.44
Permanent Ineff=
       F       F
Bank Sta=243.7,272.9
XS Rating Curve= 0 ,0
Exp/Cntr=0.3,0.1

Type RM Length L Ch R = 1 ,35760.7 ,537.8,528.9,519.5
XS GIS Cut Line= 2
     1949476.485      394973.816     1949428.742      395420.864
#Sta/Elev= 21
       0 1900.97    58.6  1898.8      88 1897.86    97.7 1897.66   107.5 1897.59
   136.8 1897.57   146.6 1897.09   156.4 1895.33   159.7 1894.58   166.2 1893.11
   175.9 1892.35   185.7 1893.64   195.5 1895.48   205.2 1895.76     215 1895.13
   224.8 1895.02   244.3 1895.78   263.9 1896.42   283.4 1896.87   371.4  1898.1
   449.6 1898.96
#Mann= 3 , 0 , 0
       0      .1       0   159.7    .045       0   185.7     .08       0
Bank Sta=159.7,185.7
XS Rating Curve= 0 ,0
Exp/Cntr=0.3,0.1

Type RM Length L Ch R = 1 ,35231.8 ,539,555.5,571.8
XS GIS Cut Line= 2
     1948955.652      395138.746     1949059.819      395598.816
#Sta/Elev= 30
       0  1893.3    39.3 1893.38      59 1893.09    78.6  1892.6    98.3 1892.54
   117.9 1892.78   127.8 1892.75   137.6 1892.47   147.4 1891.69   157.2 1890.37
   167.1 1888.59   176.9 1886.18   196.6 1879.44   206.4 1877.66   216.2 1877.58
     226 1878.84   255.5 1884.33   265.3 1885.87   275.2 1886.92     285 1887.39
   314.5 1887.83     344 1887.84   383.3  1888.1   402.9 1887.92   422.6 1887.52
   432.4 1887.94   442.2 1889.94   452.1 1893.11   461.9 1896.85   471.7 1901.24
#Mann= 3 , 0 , 0
       0      .1       0   196.6    .045       0     226      .1       0
Bank Sta=196.6,226
XS Rating Curve= 0 ,0
Exp/Cntr=0.3,0.1

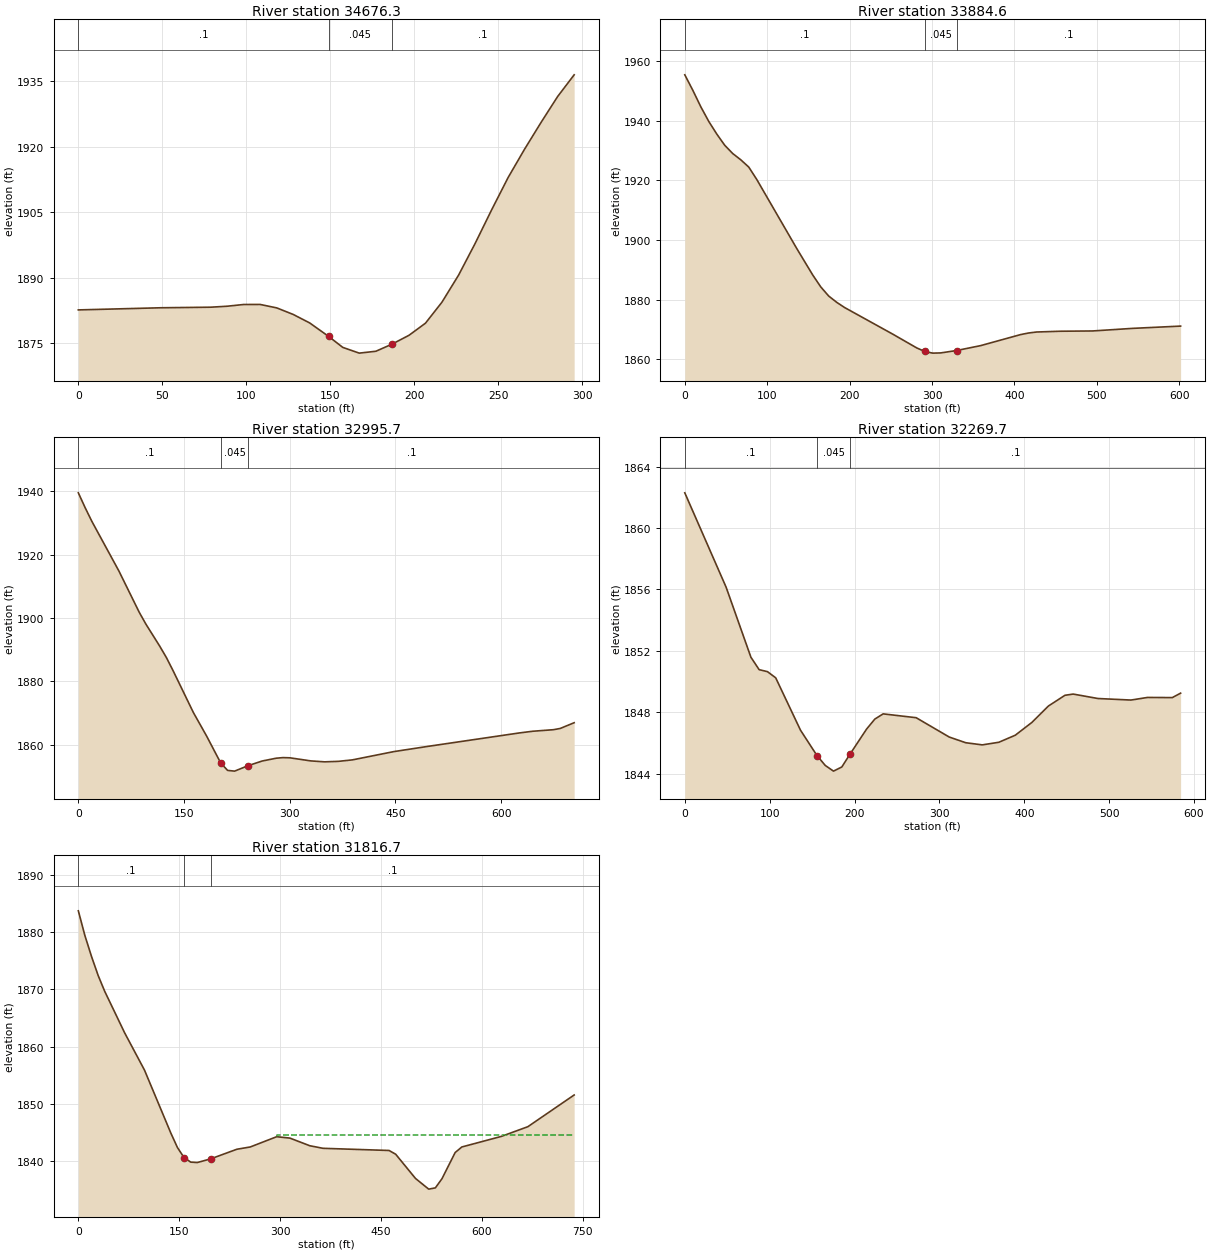
Type RM Length L Ch R = 1 ,34676.3 ,785.7,791.7,797.7
XS GIS Cut Line= 2
     1948543.326      395273.295     1948404.437      395533.711
#Sta/Elev= 25
       0 1882.64    49.2 1883.13    78.7 1883.26    88.5 1883.48    98.4 1883.88
   108.2 1883.89   118.1  1883.1   127.9  1881.6   137.7 1879.66   148.91876.593
   157.4 1874.06   167.2 1872.75   177.1 1873.18   186.71874.806   196.8 1876.83
   206.6  1879.6   216.4  1884.4   226.3 1890.59   236.1  1897.8     246 1905.55
   255.8 1912.94   265.6 1919.43   275.5 1925.61   285.3 1931.49   295.1 1936.44
#Mann= 3 , 0 , 0
       0      .1       0   148.9    .045       0   186.7      .1       0
Bank Sta=148.9,186.7
XS Rating Curve= 0 ,0
Exp/Cntr=0.3,0.1

Type RM Length L Ch R = 1 ,33884.6 ,911,888.9,866.7
XS GIS Cut Line= 2
     1948382.735      394509.406     1947961.728      394939.093
#Sta/Elev= 30
       0 1955.36     9.7  1950.2    19.4 1944.66    29.1 1939.73    38.8 1935.51
    48.5 1931.73    58.2 1928.96    67.9 1926.88    77.6 1924.44    87.3 1920.29
   135.8 1897.15   155.2 1888.27   164.9 1884.29   174.6  1881.2   184.4 1879.08
     194 1877.33   252.3 1868.43   281.4 1863.81   291.1 1862.62   300.8 1862.06
   310.5 1862.13   329.9 1862.94     359 1864.58   407.5 1868.28   417.2 1868.81
   426.9 1869.14     456  1869.4   494.8 1869.49   543.4 1870.36   601.6 1871.12
#Mann= 3 , 0 , 0
       0      .1       0   291.1    .045       0   329.9      .1       0
Bank Sta=291.1,329.9
XS Rating Curve= 0 ,0
Exp/Cntr=0.3,0.1

Type RM Length L Ch R = 1 ,32995.7 ,725.2,726.1,726.9
XS GIS Cut Line= 3
     1947393.152      394309.753     1947397.492      394492.045
      1947514.68      394999.857
#Sta/Elev= 30
       0 1939.57     9.6 1934.91    19.2 1930.56    57.6 1914.87    86.4 1901.85
      96 1898.06   115.2 1891.25   124.8 1887.61   134.4 1883.42   163.2  1870.2
   182.3 1862.64     202 1854.26   211.8 1851.91   221.7 1851.68   241.3 1853.44
     261 1854.88   280.7 1855.76   290.5 1855.95   300.3 1855.88   329.8 1854.91
   349.5 1854.61   369.2 1854.77   388.8 1855.23   447.8 1857.85     497 1859.53
   624.8 1863.71   644.5 1864.27     674 1864.76   683.8 1865.16   703.5 1866.97
#Mann= 3 , 0 , 0
       0      .1       0     202    .045       0   241.3      .1       0
Bank Sta=202,241.3
XS Rating Curve= 0 ,0
Exp/Cntr=0.3,0.1

Type RM Length L Ch R = 1 ,32269.7 ,471.5,453,434.5
XS GIS Cut Line= 2
      1946683.71      394571.908     1946793.326      395145.691
#Sta/Elev= 30
       0 1862.29    48.7 1856.14    77.9 1851.58    87.6 1850.77    97.4 1850.64
   107.1 1850.24   136.3 1846.83   155.8 1845.17   165.5 1844.53   175.2 1844.16
     185 1844.43   194.7 1845.27   214.2  1846.9   223.9 1847.55   233.7 1847.89
   272.6 1847.64   311.6 1846.38     331 1846.01   350.5 1845.87     370 1846.04
   389.4  1846.5   408.9 1847.33   428.4  1848.4   447.9  1849.1   457.6 1849.18
   486.8 1848.89   525.7 1848.79   545.2 1848.96   574.4 1848.95   584.2 1849.24
#Mann= 3 , 0 , 0
       0      .1       0   155.8    .045       0   194.7      .1       0
Bank Sta=155.8,194.7
XS Rating Curve= 0 ,0
Exp/Cntr=0.3,0.1

Type RM Length L Ch R = 1 ,31816.7 ,520.8,510.2,499.7
XS GIS Cut Line= 2
     1946173.968      394825.378     1946798.968      395216.003
#Sta/Elev= 30
       0  1883.7     9.8 1879.37    19.6 1875.74    29.5 1872.41    39.3 1869.64
    68.8 1862.43    98.3 1855.93   137.6 1844.91   147.4  1842.4   157.2 1840.65
   167.1 1839.87   176.9  1839.8   196.5 1840.43   235.8 1842.12   255.5 1842.51
   294.8  1844.3   314.5 1844.06     344 1842.73   363.6 1842.28   461.9  1841.9
   471.7 1841.25   501.2 1837.02   520.8 1835.16   530.7 1835.38   540.5 1836.97
   560.1 1841.54     570 1842.51   628.9 1844.36   668.2 1846.05     737 1851.58
#Mann= 3 , 0 , 0
       0      .1       0   157.2    .045       0   196.5      .1       0
#XS Ineff= 2 , 0
                          295.21         1844.55
Permanent Ineff=
       F       F
Bank Sta=157.2,196.5
XS Rating Curve= 0 ,0
Exp/Cntr=0.3,0.1