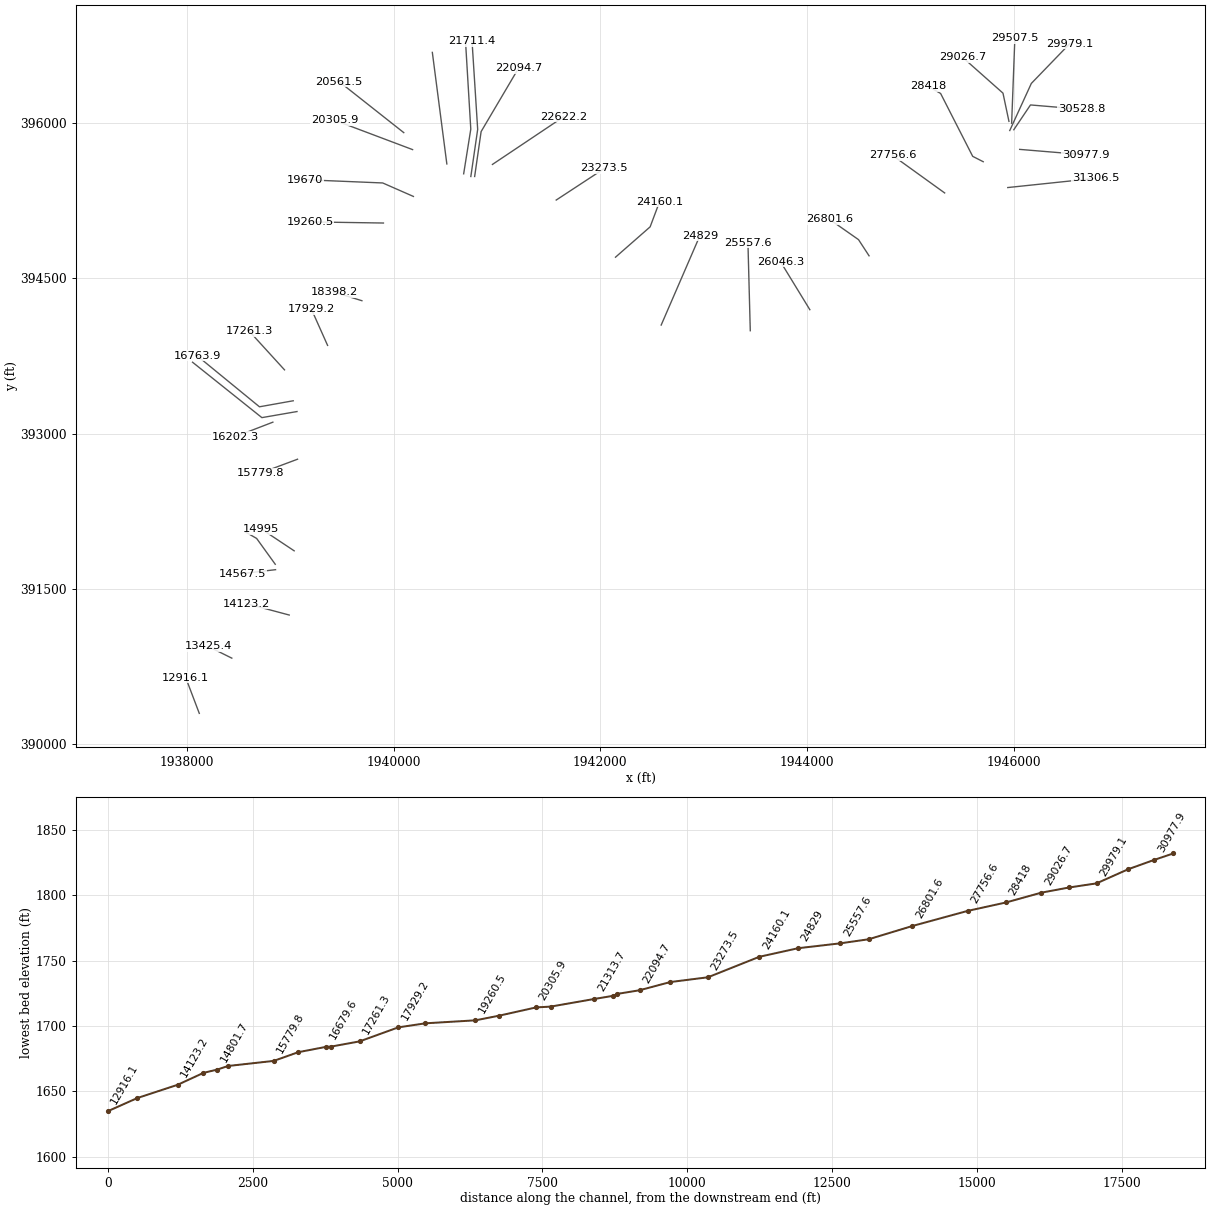
HEC-RAS study MUDDYCK2.prj: MUDDYCK2

--- MUDDYCK2.g01 (geometry) --- (continued)

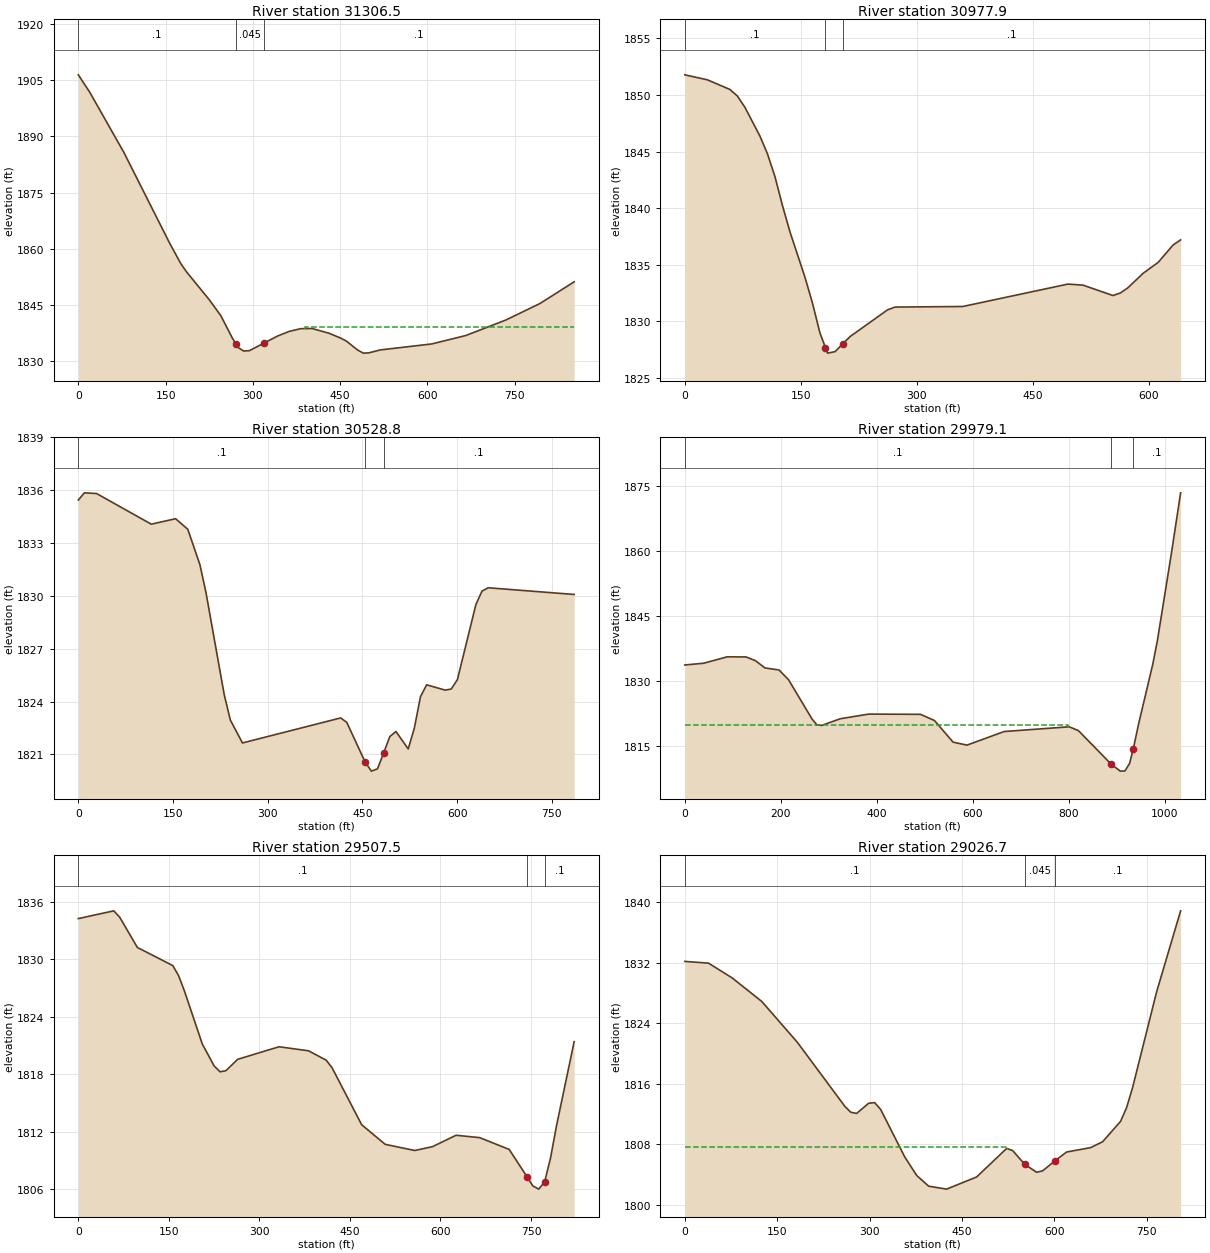
Type RM Length L Ch R = 1 ,31306.5 ,332.6,328.5,324.2
XS GIS Cut Line= 2
     1945942.197      395377.461     1946789.853      395466.437
#Sta/Elev= 30
       0 1906.45    19.6 1901.81    78.4 1885.69   156.8 1861.53   176.3 1855.97
   186.1 1853.79   225.3 1846.32   244.9 1842.12   264.5  1836.2   270.5 1834.63
   274.3 1833.64   284.1 1832.67   293.9 1832.75   319.11834.773   342.9  1836.7
   362.5  1837.9   382.1 1838.63   401.7 1838.68     431 1837.41   450.6 1836.14
   460.4 1835.36     480 1832.94   489.8  1832.1   499.6 1832.18   519.2 1832.96
   607.4 1834.55   666.2 1836.81   734.8 1840.94   793.5 1845.35   852.3 1851.15
#Mann= 3 , 0 , 0
       0      .1       0   270.5    .045       0   319.1      .1       0
#XS Ineff= 2 , 0
                          390.14         1839.04
Permanent Ineff=
       F       F
Bank Sta=270.5,319.1
XS Rating Curve= 0 ,0
Exp/Cntr=0.3,0.1

Type RM Length L Ch R = 1 ,30977.9 ,449.4,449.1,449.3
XS GIS Cut Line= 2
     1946057.337      395746.402     1946696.603      395693.357
#Sta/Elev= 30
       0 1851.78    29.2 1851.34    58.3 1850.49      68 1849.91    77.8 1848.91
    97.2 1846.37   106.9 1844.81   116.6  1842.8   126.4 1840.22   136.1  1837.9
   155.5 1833.89   165.2 1831.61   174.9 1828.96     182 1827.68   184.7 1827.19
   194.4 1827.32   204.1 1827.99   213.8 1828.65   262.4 1831.02   272.1 1831.26
   359.6 1831.31   495.7 1833.29   515.1  1833.2     554 1832.28   563.7 1832.51
   573.4 1832.97   592.9 1834.24   612.3  1835.2   631.7 1836.74   641.5  1837.2
#Mann= 3 , 0 , 0
       0      .1       0     182    .045       0   204.1      .1       0
Bank Sta=182,204.1
XS Rating Curve= 0 ,0
Exp/Cntr=0.3,0.1

Type RM Length L Ch R = 1 ,30528.8 ,528.5,549.7,570.1
XS GIS Cut Line= 3
     1946000.489      395936.354     1946161.947      396175.937
     1946656.739       396134.27
#Sta/Elev= 30
       0 1835.44     9.6 1835.85    28.9 1835.81   115.6 1834.07   154.1 1834.38
   173.4 1833.78   192.6 1831.77   202.2 1830.19   231.1 1824.39   240.8 1822.95
     260 1821.65   415.5 1823.07   425.2 1822.82   454.4 1820.56   464.2 1820.05
   473.9 1820.18   483.6 1821.08   493.4 1822.01   503.1  1822.3   522.6 1821.31
   532.3  1822.5     542 1824.28   551.8 1824.95     581 1824.65   590.7 1824.71
   600.5 1825.25   629.7  1829.5   639.4 1830.27   649.2 1830.46   785.4 1830.08
#Mann= 3 , 0 , 0
       0      .1       0   454.4    .045       0   483.6      .1       0
Bank Sta=454.4,483.6
XS Rating Curve= 0 ,0
Exp/Cntr=0.3,0.1

Type RM Length L Ch R = 1 ,29979.1 ,452.8,471.6,489.8
XS GIS Cut Line= 3
     1945961.426      395928.541     1946170.159      396383.884
     1946540.287       396766.35
#Sta/Elev= 30
       0 1833.67    39.3 1834.07    88.4 1835.55   127.7 1835.52   147.3 1834.66
     167 1832.99   196.4 1832.51   216.1 1830.28   265.2 1821.18     275 1819.88
   284.8 1819.71   324.1 1821.26     383 1822.33   491.1 1822.28   520.3 1820.85
     559 1815.86     588 1815.17   665.4 1818.31   800.9  1819.4   820.2 1818.52
     888 1810.82   907.3 1809.17     917 1809.21   926.7 1810.92   934.2 1814.18
     946 1820.27   975.1 1833.85   984.8 1839.36  1013.8 1859.36  1033.1  1873.4
#Mann= 3 , 0 , 0
       0      .1       0     888    .045       0   934.2      .1       0
#XS Ineff= 2 , 0
          797.75 1819.83
Permanent Ineff=
       F       F
Bank Sta=888,934.2
XS Rating Curve= 0 ,0
Exp/Cntr=0.3,0.1

Type RM Length L Ch R = 1 ,29507.5 ,460.5,480.7,500.5
XS GIS Cut Line= 2
     1945979.655      395998.854     1946010.773      396819.736
#Sta/Elev= 30
       0 1834.25    58.7 1835.06    68.5  1834.4    97.8 1831.24   156.5 1829.35
   166.2 1828.29     176 1826.66   205.4 1821.17   224.9 1818.89   234.7 1818.27
   244.5 1818.38     264 1819.57   332.5 1820.88   381.4 1820.46   410.7 1819.48
   420.5 1818.68   469.4 1812.75   508.5  1810.7   557.4 1810.06   586.8 1810.46
   625.9 1811.65     665  1811.4   713.9 1810.17   743.2 1807.34     753 1806.37
   762.8 1806.03   772.6 1806.79   782.4 1809.29   792.1 1812.59   821.5 1821.41
#Mann= 3 , 0 , 0
       0      .1       0   743.2    .045       0   772.6      .1       0
Bank Sta=743.2,772.6
XS Rating Curve= 0 ,0
Exp/Cntr=0.3,0.1

Type RM Length L Ch R = 1 ,29026.7 ,626.5,608.8,600.4
XS GIS Cut Line= 3
     1945953.614      396017.083      1945895.83      396289.965
      1945502.22      396638.708
#Sta/Elev= 30
       0 1832.18    38.5 1831.95      77 1829.99     125 1826.88   182.8 1821.47
   259.7 1813.02   269.3 1812.23   278.9 1812.07   298.4 1813.42   308.2  1813.5
   317.9  1812.6   356.8 1806.35   376.3 1803.88   395.8 1802.45     425 1802.06
   473.7 1803.67   522.4 1807.44   532.1 1807.17   551.6 1805.35   571.1 1804.29
   580.8 1804.48   600.3 1805.77   619.8 1806.97   658.7 1807.55   678.2 1808.33
   707.4 1811.03   717.2 1812.86   726.9 1815.51   765.9 1828.17   804.8 1838.87
#Mann= 3 , 0 , 0
       0      .1       0   551.6    .045       0   600.3      .1       0
#XS Ineff= 2 , 0
          523.94  1807.6
Permanent Ineff=
       F       F
Bank Sta=551.6,600.3
XS Rating Curve= 0 ,0
Exp/Cntr=0.3,0.1

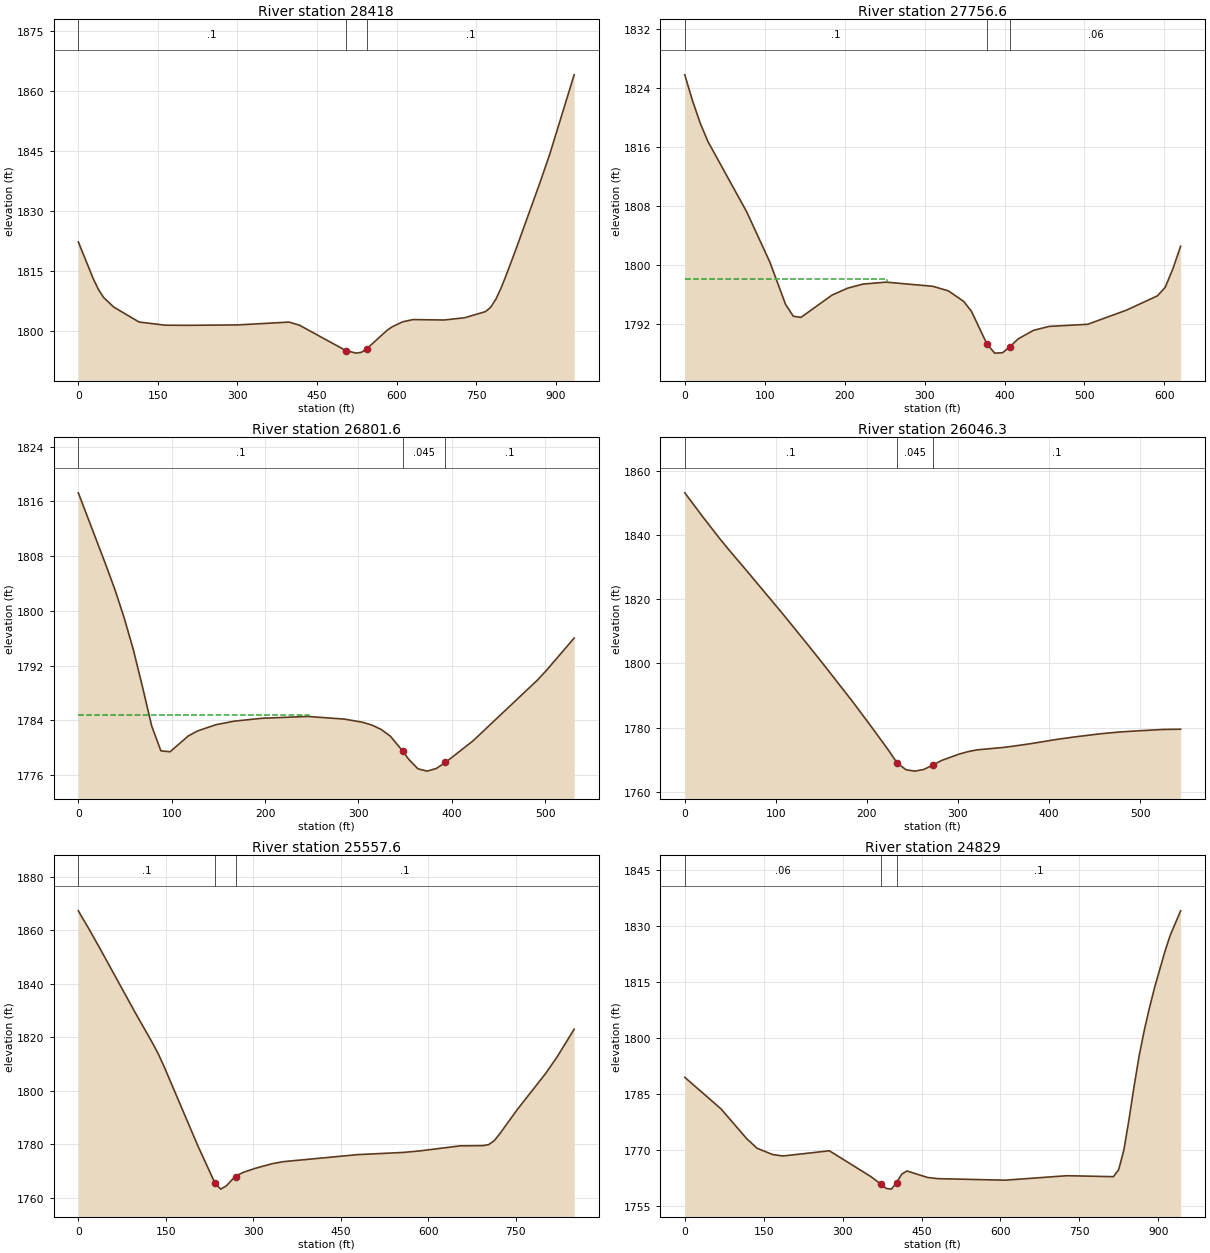
Type RM Length L Ch R = 1 ,28418   ,650.5,661.4,672.3
XS GIS Cut Line= 4
     1945704.784      395627.027     1945602.787      395679.111
     1945292.458       396286.75       1945173.1      396356.194
#Sta/Elev= 30
       0 1822.33    28.6    1813    38.2  1810.4    47.7 1808.45    66.8 1806.06
   114.5 1802.33   163.3 1801.54   202.2  1801.5   299.7  1801.6   397.2 1802.31
   416.7 1801.55   504.4  1795.2   523.9 1794.56   533.6 1794.76   543.4 1795.59
   582.4 1800.29   592.1 1801.16   611.6 1802.38   631.1 1802.94   689.6 1802.83
   728.6  1803.4   767.6 1804.92   777.3 1805.99   787.1 1807.98   796.8 1810.72
     806 1813.77   824.4 1820.23   870.5 1837.16   888.9 1844.24   934.9 1864.05
#Mann= 3 , 0 , 0
       0      .1       0   504.4    .045       0   543.4      .1       0
Bank Sta=504.4,543.4
XS Rating Curve= 0 ,0
Exp/Cntr=0.3,0.1

Type RM Length L Ch R = 1 ,27756.6 ,955.4,954.9,954.3
XS GIS Cut Line= 2
      1945331.52      395325.378     1944828.048      395687.791
#Sta/Elev= 30
       0 1825.76     9.7 1822.25    19.4 1819.19    29.1 1816.71    77.5 1807.22
   106.6 1800.39     126 1794.73   135.7 1793.11   145.4 1792.96   184.2 1795.97
   203.6  1796.9   222.9 1797.46     252 1797.72   310.2 1797.16   329.6 1796.55
   348.9 1795.12   358.6 1793.78     378 1789.35   387.7 1788.12   397.4 1788.17
   407.1 1789.01   416.8 1790.03   436.2  1791.2   455.6 1791.73     504 1792.02
   552.5 1793.93   591.3 1795.87     601 1797.02   610.6 1799.52   620.3 1802.58
#Mann= 3 , 0 , 0
       0      .1       0     378    .045       0   407.1     .06       0
#XS Ineff= 2 , 0
          253.38 1798.18
Permanent Ineff=
       F       F
Bank Sta=378,407.1
XS Rating Curve= 0 ,0
Exp/Cntr=0.3,0.1

Type RM Length L Ch R = 1 ,26801.6 ,764.9,755.4,745.8
XS GIS Cut Line= 3
     1944600.183      394717.739     1944498.187      394873.989
     1944216.069      395071.472
#Sta/Elev= 30
       0 1817.26    29.5 1806.71    39.3 1803.06    49.1 1798.97    58.9 1794.32
    68.8 1788.83    78.6 1783.14    88.4 1779.52    98.2 1779.38   117.8  1781.7
   127.7 1782.43   147.3 1783.34     167 1783.86   196.4 1784.28   245.6 1784.55
     285 1784.16   304.7 1783.69   314.5 1783.28   324.3 1782.65   334.2 1781.66
   347.3  1779.5   353.9 1778.27   363.7 1776.89   373.5 1776.55   383.4 1776.94
   393.2 1777.83   422.7 1780.98   491.6 1789.86   501.4  1791.3     531 1796.02
#Mann= 3 , 0 , 0
       0      .1       0   347.3    .045       0   393.2      .1       0
#XS Ineff= 2 , 0
          246.76 1784.81
Permanent Ineff=
       F       F
Bank Sta=347.3,393.2
XS Rating Curve= 0 ,0
Exp/Cntr=0.3,0.1

Type RM Length L Ch R = 1 ,26046.3 ,500.6,488.7,476.9
XS GIS Cut Line= 2
     1944027.267      394196.906     1943742.978      394661.316
#Sta/Elev= 30
       0 1853.21    19.4 1845.86    38.9 1838.73    48.6 1835.38    68.1 1828.86
     107 1815.65   136.1 1805.47   155.6  1798.5   184.8 1787.88   204.2  1780.5
   223.6 1772.96   233.4 1768.84   243.1  1766.8   252.8 1766.39   262.5 1766.92
   272.3 1768.27     282 1769.72   301.4 1771.72   311.2 1772.48   320.9 1773.02
     350 1773.79   359.8 1774.14   379.2 1774.93   408.4 1776.28   427.8 1777.05
     457 1778.06   476.4 1778.57   495.9 1778.93   525.1 1779.39   544.5 1779.47
#Mann= 3 , 0 , 0
       0      .1       0   233.4    .045       0   272.3      .1       0
Bank Sta=233.4,272.3
XS Rating Curve= 0 ,0
Exp/Cntr=0.3,0.1

Type RM Length L Ch R = 1 ,25557.6 ,738.4,728.6,718.7
XS GIS Cut Line= 2
      1943451.01      393993.645     1943428.308      394843.607
#Sta/Elev= 30
       0 1867.19    19.6  1859.9    39.1 1852.34    97.7 1829.12     127 1817.92
   136.8 1813.91   146.6 1809.29   205.2 1779.34   234.6 1765.39   244.3 1763.28
   254.1 1764.55   263.9 1766.86   269.7 1767.89   273.6 1768.58   283.4 1769.58
     303 1771.02   332.3 1772.77   351.8 1773.54   478.9 1776.16   557.1 1776.98
   586.4 1777.57   654.8 1779.44   693.9 1779.52   703.7  1779.9   713.4  1781.4
   723.2 1784.07   752.5 1792.92   801.4 1806.47     821 1812.63   850.3 1822.99
#Mann= 3 , 0 , 0
       0      .1       0   234.6    .045       0   269.7      .1       0
Bank Sta=234.6,269.7
XS Rating Curve= 0 ,0
Exp/Cntr=0.3,0.1

Type RM Length L Ch R = 1 ,24829   ,677.8,668.9,660.2
XS GIS Cut Line= 2
      1942589.03      394048.333     1942963.898      394913.052
#Sta/Elev= 30
       0 1789.52    68.7 1781.08   117.8 1773.05   137.4  1770.5   166.9 1768.82
   186.5 1768.43   274.9 1769.82   353.4 1762.93   373.1 1760.84   382.8 1759.74
   392.7 1759.54   402.5 1761.26   412.3 1763.53   422.2 1764.41   461.4 1762.67
   481.1 1762.35   608.7 1761.94   726.5 1763.14   814.8 1762.88   824.7 1764.75
   834.5 1769.96   844.3 1778.13   854.1 1787.17   863.9 1795.46   873.8 1802.39
   883.6 1808.36   893.4 1813.81     913 1823.45   922.8 1827.64   942.5 1834.18
#Mann= 3 , 0 , 0
       0     .06       0   373.1    .045       0   402.5      .1       0
Bank Sta=373.1,402.5
XS Rating Curve= 0 ,0
Exp/Cntr=0.3,0.1

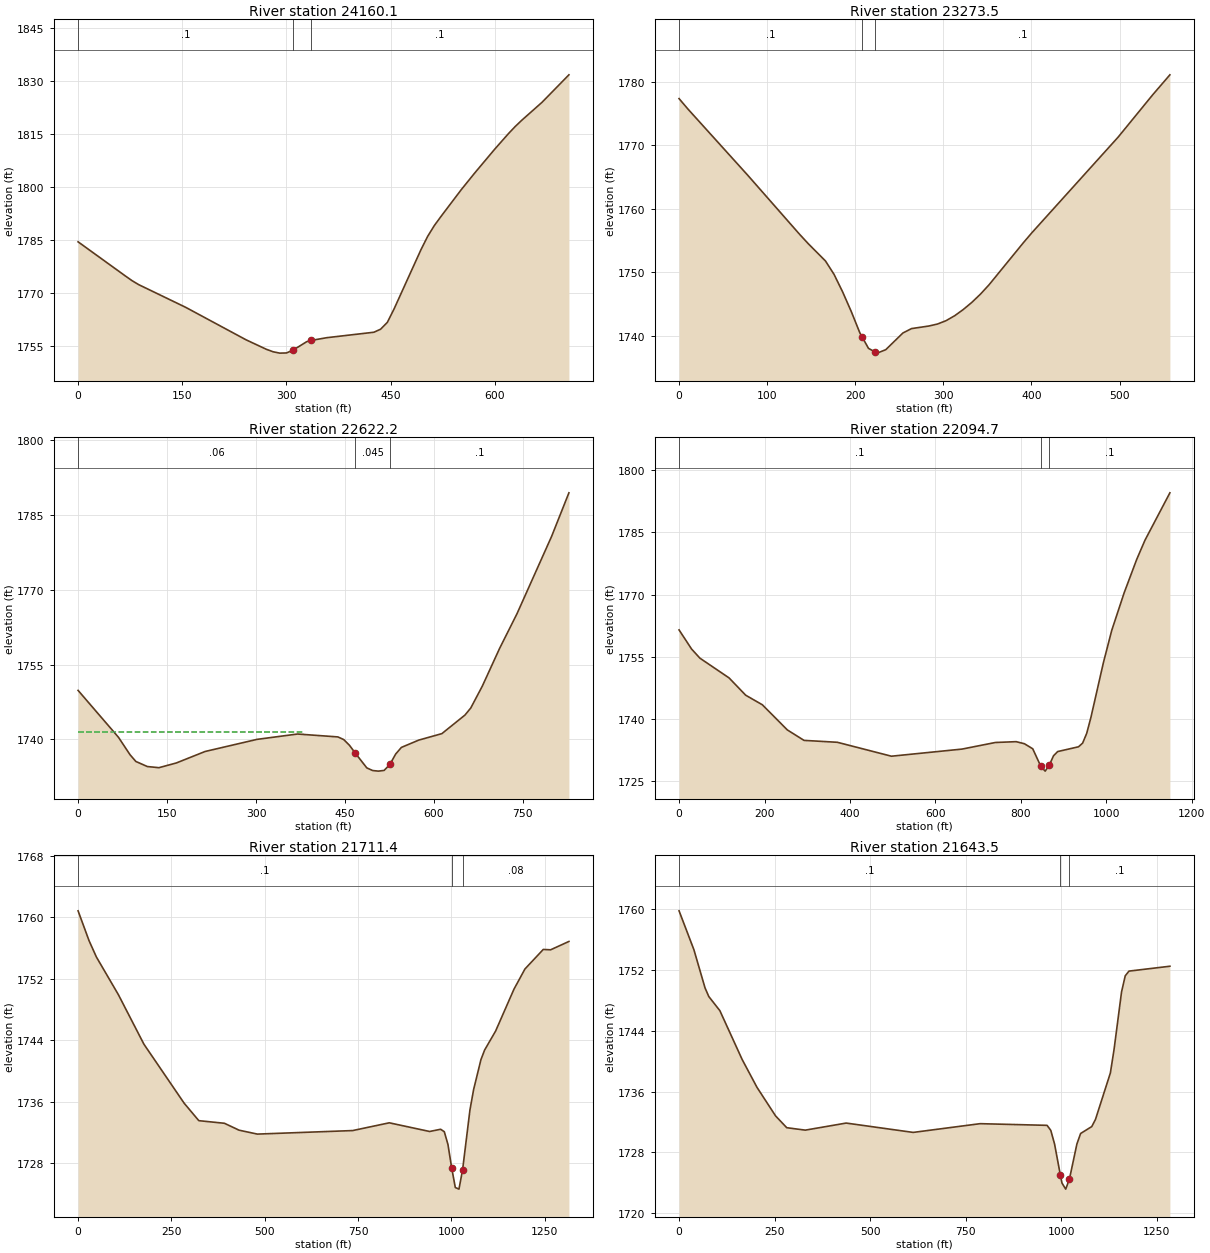
Type RM Length L Ch R = 1 ,24160.1 ,890.4,886.6,882.3
XS GIS Cut Line= 3
     1942147.027       394704.34     1942482.128      394997.687
     1942574.111      395242.534
#Sta/Elev= 30
       0 1784.48    67.8 1774.86    77.4 1773.53    87.1 1772.38   154.9 1765.95
     242 1756.74   271.1 1754.07   280.8 1753.37   290.4 1752.98   300.1 1753.03
   309.8 1753.85   329.2 1756.21   335.8 1756.58   358.2 1757.35     426 1758.89
   435.7 1759.75   445.4 1761.69     455 1765.45   493.8 1782.24   503.5 1786.04
   513.2 1789.12   522.9 1791.72   551.9 1799.25   571.3 1803.97   600.4 1810.78
   619.7 1815.07   629.4 1817.08   639.1  1818.9   668.2 1823.97   706.9 1831.74
#Mann= 3 , 0 , 0
       0      .1       0   309.8    .045       0   335.8      .1       0
Bank Sta=309.8,335.8
XS Rating Curve= 0 ,0
Exp/Cntr=0.3,0.1

Type RM Length L Ch R = 1 ,23273.5 ,650.9,651.3,651.6
XS GIS Cut Line= 2
     1941573.405      395256.666     1942039.388      395561.978
#Sta/Elev= 30
       0 1777.34     9.8 1775.74    78.2 1765.25   136.8    1756   146.6 1754.53
   166.2  1751.8   175.9  1749.7   185.7 1746.93   195.5 1743.84   205.2  1740.5
   207.9 1739.83     215 1738.06   222.9 1737.46   224.8 1737.31   234.6 1737.85
   254.1 1740.48   263.9 1741.17   283.4 1741.57   293.2 1741.88     303 1742.41
   312.8 1743.19   322.5 1744.16   332.3 1745.29   342.1 1746.59   351.8 1748.05
   390.9 1754.69   400.7 1756.28   498.4 1771.29   537.6 1777.94   557.1 1781.08
#Mann= 3 , 0 , 0
       0      .1       0   207.9    .045       0   222.9      .1       0
Bank Sta=207.9,222.9
XS Rating Curve= 0 ,0
Exp/Cntr=0.3,0.1

Type RM Length L Ch R = 1 ,22622.2 ,517.3,527.5,537.5
XS GIS Cut Line= 2
      1940956.52      395600.986     1941644.454      396061.055
#Sta/Elev= 30
       0 1749.83    68.2 1740.41    87.6 1736.93    97.4 1735.58   116.8 1734.56
   136.3 1734.33   165.5 1735.27   214.2 1737.58   301.8 1740.01     370 1741.08
   438.1  1740.5   447.9 1739.97   457.6 1738.82   467.4 1737.25   486.8 1734.29
   496.6 1733.76   506.3 1733.64     516 1733.78   525.8 1734.99   535.5 1737.07
   545.2  1738.4   574.4 1739.86   613.4 1741.16   652.3 1744.88   662.1  1746.3
   681.6 1750.69   710.8 1758.27     740 1765.19   798.4 1780.71   827.6 1789.45
#Mann= 3 , 0 , 0
       0     .06       0   467.4    .045       0   525.8      .1       0
#XS Ineff= 2 , 0
          378.87 1741.49
Permanent Ineff=
       F       F
Bank Sta=467.4,525.8
XS Rating Curve= 0 ,0
Exp/Cntr=0.3,0.1

Type RM Length L Ch R = 1 ,22094.7 ,369.2,383.3,397.3
XS GIS Cut Line= 3
     1940784.338      395484.194       1940846.9      395918.442
     1941208.256      396529.805
#Sta/Elev= 30
       0 1761.46    29.2 1756.86    48.8 1754.64     117 1749.88     156  1745.7
     195 1743.39   253.5 1737.32   292.5  1734.8   370.5 1734.34   497.1 1730.98
   662.5  1732.7   740.3 1734.29     789 1734.49   808.4 1733.99   827.9 1732.77
   846.9  1728.5     857 1727.38   866.8 1728.87   876.5 1731.08   886.2  1732.1
   934.9 1733.25   944.6 1734.13   954.3 1736.53   964.1 1740.37   993.2 1753.53
  1012.7 1761.32  1041.9 1770.43  1071.1 1778.44  1090.5 1783.09  1148.9 1794.54
#Mann= 3 , 0 , 0
       0      .1       0   846.9    .045       0   866.8      .1       0
Bank Sta=846.9,866.8
XS Rating Curve= 0 ,0
Exp/Cntr=0.3,0.1

Type RM Length L Ch R = 1 ,21711.4 ,67.8,67.9,67.9
XS GIS Cut Line= 3
     1940747.446      395484.194     1940813.625      395939.992
     1940759.037      396792.392
#Sta/Elev= 30
       0 1760.86    29.4 1756.97      49 1754.85   107.8 1749.95   176.4 1743.48
   284.2 1735.79   323.4 1733.52     392 1733.18   431.2 1732.28   480.2 1731.77
   735.5 1732.23   833.6 1733.24   941.6 1732.11   971.1  1732.4   980.9 1732.08
   990.7 1730.42  1000.6 1727.39  1010.4 1724.81  1020.2  1724.6    1030 1727.15
  1049.6 1734.91  1059.5 1737.59  1079.1 1741.48  1088.9 1742.72  1118.4  1745.2
  1167.5 1750.65  1196.9 1753.28    1246 1755.83  1265.6 1755.78  1314.7 1756.87
#Mann= 3 , 0 , 0
       0      .1       0  1000.6    .045       0    1030     .08       0
Bank Sta=1000.6,1030
XS Rating Curve= 0 ,0
Exp/Cntr=0.3,0.1

Type RM Length L Ch R = 1 ,21643.5 ,328.5,329.8,331.2
XS GIS Cut Line= 3
     1940678.001      395510.236     1940746.982      395942.196
     1940696.103      396788.052
#Sta/Elev= 30
       0 1759.77    38.9 1754.65      68 1749.63    77.8  1748.5   106.9 1746.63
   165.2 1740.21   204.1 1736.54   252.7 1732.79   281.9 1731.24   330.5 1730.92
   437.4 1731.85   612.8 1730.62   788.1 1731.77   963.4 1731.55   973.1 1730.88
   982.9  1729.1   998.1 1725.01  1002.4 1723.95  1012.1 1723.16  1021.8 1724.47
  1041.3 1729.08  1051.1 1730.48  1080.3 1731.39    1090 1732.33    1129 1738.44
  1138.7 1741.55  1158.2 1749.09  1167.9 1751.22  1177.7 1751.84  1284.8 1752.48
#Mann= 3 , 0 , 0
       0      .1       0   998.1    .045       0  1021.8      .1       0
Bank Sta=998.1,1021.8
XS Rating Curve= 0 ,0
Exp/Cntr=0.3,0.1

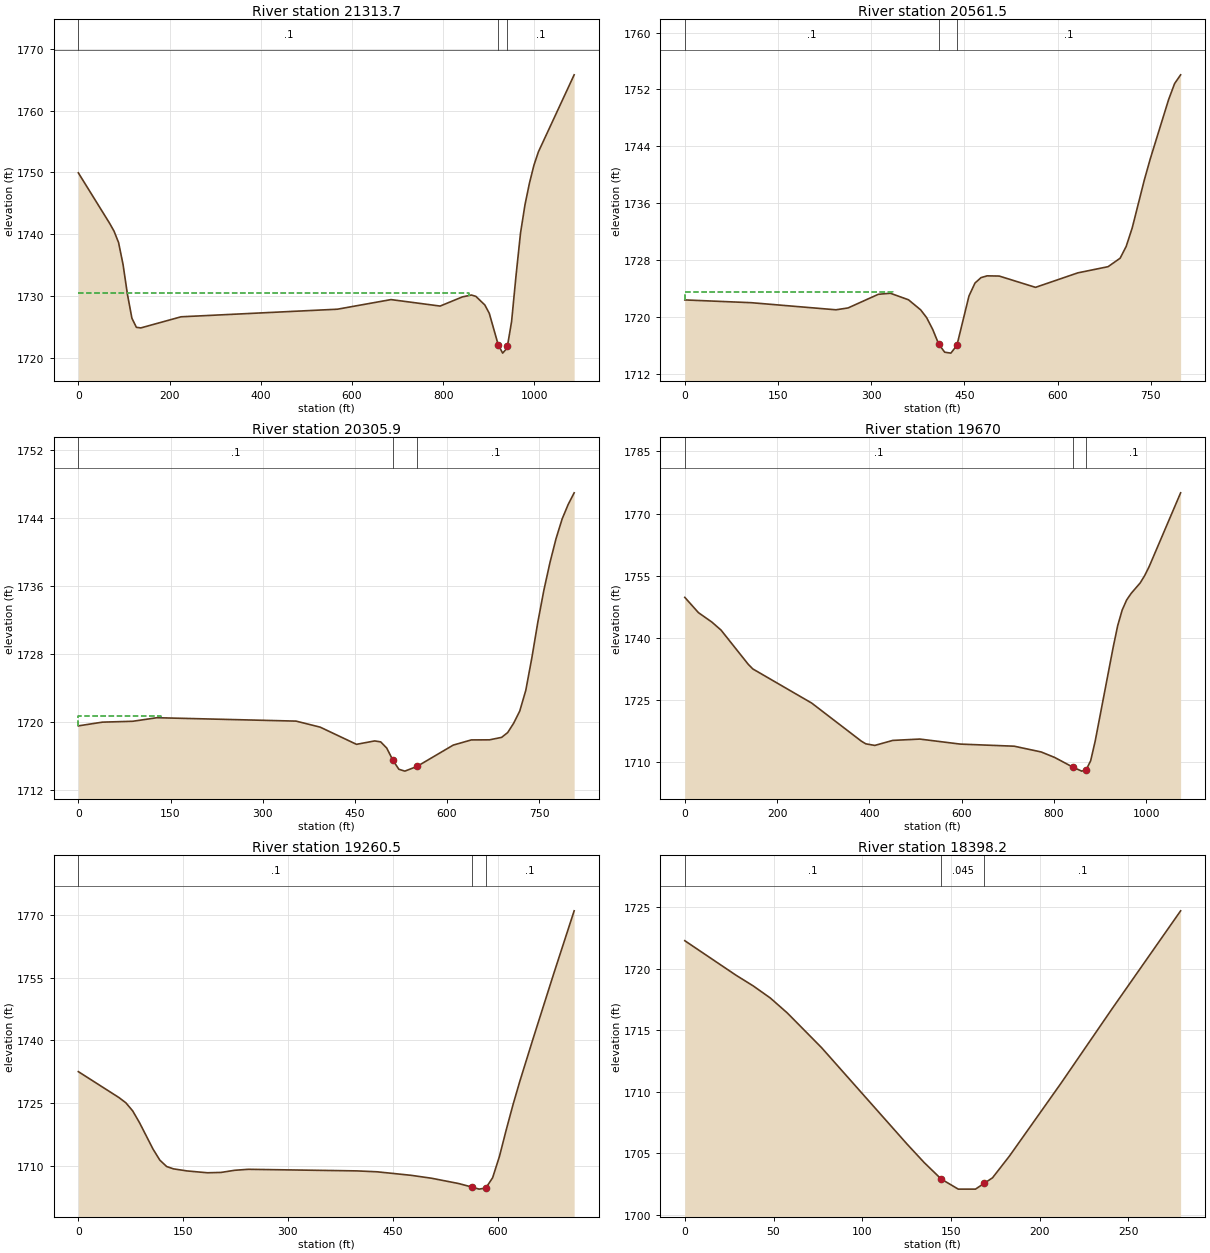
Type RM Length L Ch R = 1 ,21313.7 ,734.5,752.2,769.8
XS GIS Cut Line= 2
     1940515.241      395605.722     1940374.923      396683.885
#Sta/Elev= 30
       0 1749.94    68.6 1741.76    78.4 1740.47    88.2 1738.65      98 1735.11
   107.8  1730.2   117.5 1726.37   127.3 1724.89   137.1  1724.8   225.3  1726.6
   568.1 1727.83   685.7 1729.39   793.4 1728.34   842.4 1729.83     862 1730.13
   871.8 1729.91   891.4 1728.52   901.2 1727.16   920.7 1722.08   930.5 1720.71
   940.3 1721.53     941 1721.84   950.1 1725.84   959.9 1733.33   969.7 1740.18
   979.5 1744.78   989.3 1748.28   999.1 1751.18  1008.9 1753.34  1087.3 1765.83
#Mann= 3 , 0 , 0
       0      .1       0   920.7    .045       0     941      .1       0
#XS Ineff= 2 , 0
           856.9 1730.47
Permanent Ineff=
       F       F
Bank Sta=920.7,941
XS Rating Curve= 0 ,0
Exp/Cntr=0.3,0.1

Type RM Length L Ch R = 1 ,20561.5 ,249,255.6,262.8
XS GIS Cut Line= 2
     1940098.559      395908.259     1939471.843        396402.5
#Sta/Elev= 30
       0 1722.36   107.1 1721.97   243.3 1720.97   262.8 1721.23   311.5 1723.15
   330.9  1723.3   360.1 1722.38   379.6 1720.97   389.3 1719.87   399.1 1718.21
   408.8 1716.13   418.4    1715   428.3 1714.87     438 1715.95   457.5 1722.92
   467.2 1724.74   476.9  1725.5   486.7 1725.75   506.2 1725.72   564.6 1724.13
   632.7 1726.17   681.4 1727.04   700.8 1728.23   710.6  1729.9   720.3 1732.51
   739.8 1739.26   749.5 1742.27   778.7 1750.52   788.4  1752.8   798.2 1754.05
#Mann= 3 , 0 , 0
       0      .1       0   408.8    .045       0     438      .1       0
#XS Ineff= 2 , 0
          334.65 1723.43
Permanent Ineff=
       F       F
Bank Sta=408.8,438
XS Rating Curve= 0 ,0
Exp/Cntr=0.3,0.1

Type RM Length L Ch R = 1 ,20305.9 ,626.4,635.8,644
XS GIS Cut Line= 2
     1940183.951      395744.215     1939428.742      396028.503
#Sta/Elev= 30
       0 1719.54    39.4 1719.98    88.6 1720.08   127.9  1720.5   354.3  1720.1
   393.6 1719.39   452.7 1717.37   482.2 1717.77     492 1717.66   501.9 1716.93
   511.7 1715.53   521.6 1714.44   531.4 1714.22   551.1 1714.77   610.1 1717.28
   639.6 1717.89   669.2  1717.9   688.9 1718.19   698.7 1718.75   708.5 1719.86
   718.4 1721.29   728.2 1723.72   738.1 1727.56   747.9 1731.78   757.7 1735.52
   767.6 1738.76   777.4 1741.55   787.3 1743.86   797.1 1745.56   806.9 1746.94
#Mann= 3 , 0 , 0
       0      .1       0   511.7    .045       0   551.1      .1       0
#XS Ineff= 2 , 0
          135.21 1720.69
Permanent Ineff=
       F       F
Bank Sta=511.7,551.1
XS Rating Curve= 0 ,0
Exp/Cntr=0.3,0.1

Type RM Length L Ch R = 1 ,19670   ,409.5,409.6,409.9
XS GIS Cut Line= 3
     1940191.804      395291.589     1939894.929      395421.797
     1939144.929      395453.047
#Sta/Elev= 30
       0 1749.82    29.5 1746.14    58.9 1743.84    78.6 1741.92   137.5 1733.68
   147.4 1732.56   275.1 1724.32   382.7 1715.14   392.4 1714.49   411.9 1714.11
   450.9 1715.32   509.4 1715.64   597.1 1714.43   714.1 1713.92   772.6 1712.53
   801.9  1711.2   840.9 1708.89   860.4 1707.91   870.1 1708.26   879.8 1710.41
   889.6 1715.15   928.6 1737.78   938.3 1742.96   948.1 1746.76   957.8 1749.19
   967.6 1750.78   987.1 1753.29   996.8 1755.06  1006.6 1757.24  1074.8 1775.03
#Mann= 3 , 0 , 0
       0      .1       0   840.9    .045       0   870.1      .1       0
Bank Sta=840.9,870.1
XS Rating Curve= 0 ,0
Exp/Cntr=0.3,0.1

Type RM Length L Ch R = 1 ,19260.5 ,869,862.3,854.9
XS GIS Cut Line= 2
     1939901.833       395034.58     1939192.197       395045.43
#Sta/Elev= 30
       0 1732.51    58.3 1726.28    68.1 1725.03    77.8  1723.1    87.5  1720.3
   106.9 1713.95   116.7 1711.29   126.4 1709.77   136.1 1709.21   155.6 1708.71
   184.7 1708.27   204.2 1708.35   223.6 1708.86     243  1709.1   398.6 1708.72
   427.8  1708.5   476.4 1707.66   505.6 1706.96   544.4 1705.69   563.9 1704.82
   573.6 1704.35   583.3 1704.62     593 1707.08   602.8 1712.22   612.5 1718.57
   622.2  1724.6   631.9 1730.18   651.4 1740.67   680.6 1756.06   709.7 1771.05
#Mann= 3 , 0 , 0
       0      .1       0   563.9    .045       0   583.3      .1       0
Bank Sta=563.9,583.3
XS Rating Curve= 0 ,0
Exp/Cntr=0.3,0.1

Type RM Length L Ch R = 1 ,18398.2 ,488.2,469,449.8
XS GIS Cut Line= 2
     1939693.499      394283.711     1939426.572      394366.177
#Sta/Elev= 17
       0 1722.27    28.9 1719.46    38.5  1718.6    48.2 1717.61    57.8 1716.39
    77.1 1713.57   125.2 1705.74   134.9 1704.23   144.5 1702.89   154.1 1702.07
   163.8 1702.07   168.6 1702.53   173.4 1702.99     183 1704.77   211.9 1710.66
   240.8 1716.74   279.4  1724.7
#Mann= 3 , 0 , 0
       0      .1       0   144.5    .045       0   168.6      .1       0
Bank Sta=144.5,168.6
XS Rating Curve= 0 ,0
Exp/Cntr=0.3,0.1

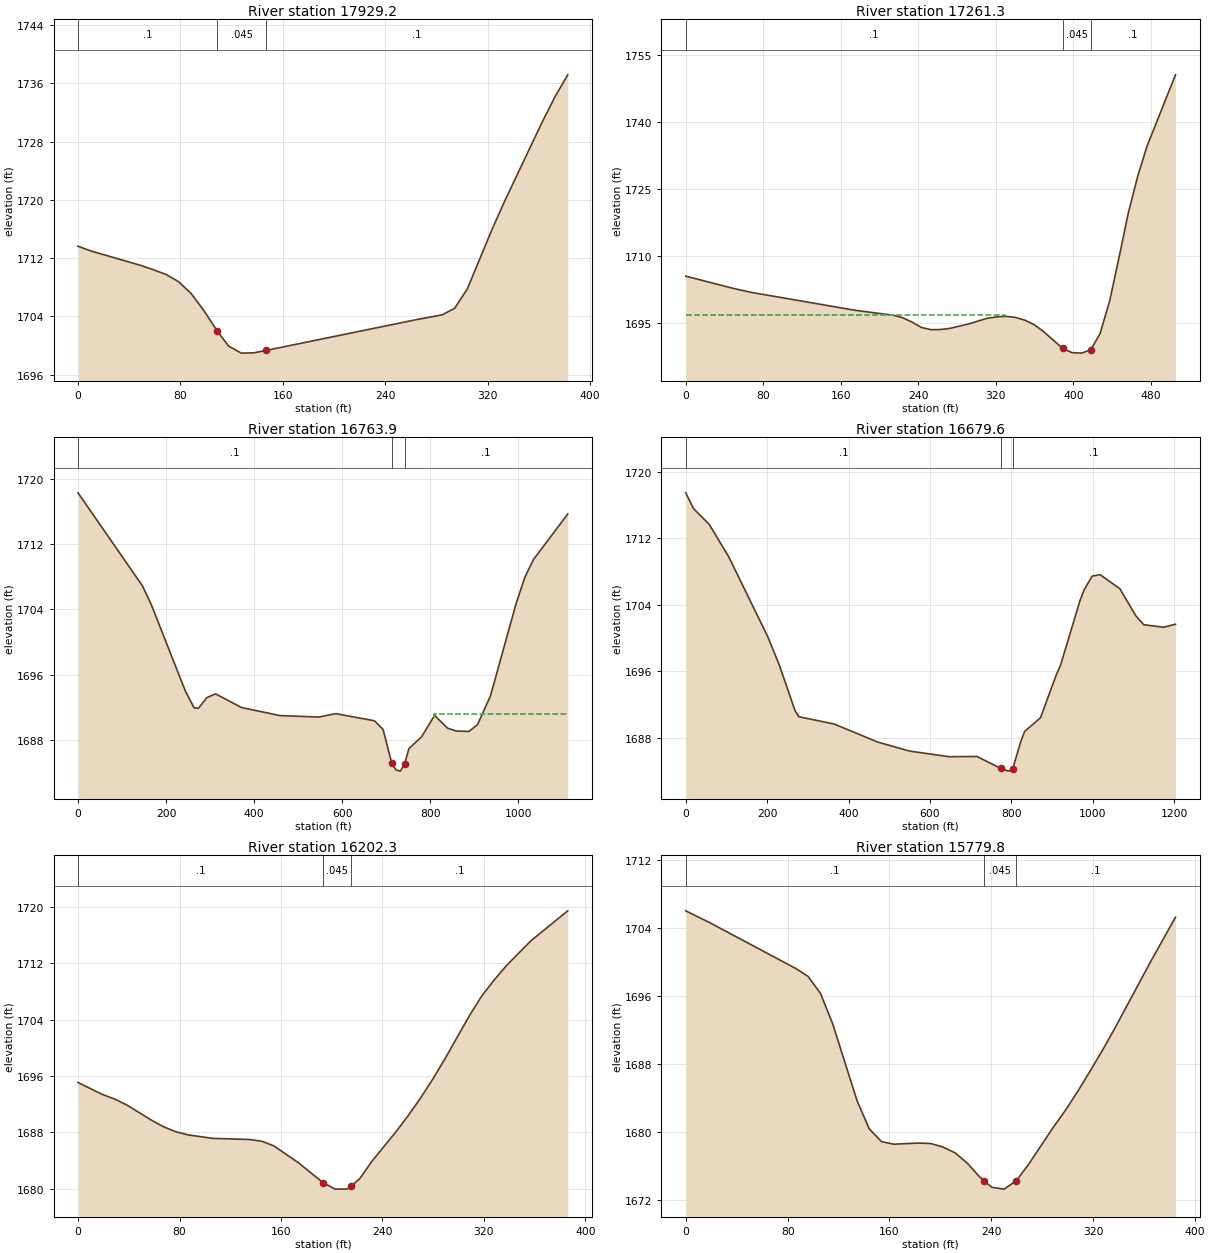
Type RM Length L Ch R = 1 ,17929.2 ,660.2,667.9,675.3
XS GIS Cut Line= 2
     1939361.468      393851.854     1939205.218      394201.246
#Sta/Elev= 22
       0 1713.64     9.8    1713    49.1    1711    58.9 1710.41    68.7 1709.77
    78.5 1708.78    88.3 1707.16    98.1 1704.87   108.8 1701.98   117.8 1699.91
   127.6 1698.96   137.4    1699   147.2 1699.34     265 1703.58   284.6 1704.22
   294.4 1705.13   304.2 1707.77   323.9  1716.1   333.7 1719.94   363.1 1730.82
   372.9  1734.2   382.7 1737.17
#Mann= 3 , 0 , 0
       0      .1       0   108.8    .045       0   147.2      .1       0
Bank Sta=108.8,147.2
XS Rating Curve= 0 ,0
Exp/Cntr=0.3,0.1

Type RM Length L Ch R = 1 ,17261.3 ,494.2,497.4,500.4
XS GIS Cut Line= 2
     1938944.801      393615.309     1938604.089      393988.573
#Sta/Elev= 30
       0 1705.46    48.6 1702.74      68 1701.81   174.9 1697.81   213.8 1696.72
   223.5 1696.18   233.2 1695.22     243 1693.99   252.7 1693.48   262.4 1693.51
   272.1 1693.75   291.6 1694.74     311 1696.02   320.7 1696.34   330.4 1696.47
   340.2 1696.23   349.9 1695.61   359.6  1694.6   369.3 1693.05   388.8 1689.31
   398.5 1688.34   408.2 1688.23   417.9 1688.94   427.6 1692.62   437.4 1699.85
   447.1 1709.58   456.8 1719.67   466.5 1727.88   476.2 1734.64   505.4 1750.51
#Mann= 3 , 0 , 0
       0      .1       0   388.8    .045       0   417.9      .1       0
#XS Ineff= 2 , 0
          329.58 1696.86
Permanent Ineff=
       F       F
Bank Sta=388.8,417.9
XS Rating Curve= 0 ,0
Exp/Cntr=0.3,0.1

Type RM Length L Ch R = 1 ,16763.9 ,170.8,84.3,82.5
XS GIS Cut Line= 3
     1939029.135      393316.562     1938702.329       393258.28
     1938098.447      393752.027
#Sta/Elev= 30
       0 1718.27   146.4 1706.87     166 1704.63   244.1 1693.96   263.6 1691.94
   273.4  1691.9   292.9 1693.21   312.4 1693.66     371 1691.99   458.7    1691
   546.5 1690.82   585.5 1691.24   673.2 1690.36   692.7  1689.3   712.2 1685.21
     722 1684.34   731.7  1684.2   741.5 1685.06   751.2 1686.94   780.5 1688.43
   809.7 1691.03     839 1689.46   858.5 1689.11   887.7 1689.06   907.2  1689.9
   936.5 1693.41     995 1704.76  1014.5 1707.92    1034 1710.09    1112 1715.68
#Mann= 3 , 0 , 0
       0      .1       0   712.2    .045       0   741.5      .1       0
#XS Ineff= 2 , 0
                          807.89         1691.24
Permanent Ineff=
       F       F
Bank Sta=712.2,741.5
XS Rating Curve= 0 ,0
Exp/Cntr=0.3,0.1

Type RM Length L Ch R = 1 ,16679.6 ,365.2,477.3,504.4
XS GIS Cut Line= 3
     1939065.593      393212.395     1938725.852      393153.602
     1938055.044      393689.093
#Sta/Elev= 30
       0 1717.44    19.2 1715.54    57.5 1713.66   105.4 1709.78   201.1 1700.21
   229.9 1696.76   268.2 1691.32   277.8 1690.56   364.3 1689.69   471.6 1687.52
   549.6 1686.44   647.2 1685.76   715.4 1685.79     774 1684.35   793.5 1684.03
   803.2  1684.3   822.7 1687.54   832.5 1688.79   871.5 1690.44   910.5 1695.62
   920.3 1696.68     969 1704.58   978.8  1705.8   998.3 1707.44  1017.8 1707.62
  1066.6 1705.92  1105.6 1702.68  1125.1 1701.61  1173.9  1701.3  1203.1 1701.67
#Mann= 3 , 0 , 0
       0      .1       0     774    .045       0   803.2      .1       0
Bank Sta=774,803.2
XS Rating Curve= 0 ,0
Exp/Cntr=0.3,0.1

Type RM Length L Ch R = 1 ,16202.3 ,422.8,422.5,422.3
XS GIS Cut Line= 2
     1938831.954      393109.666     1938471.711      392970.777
#Sta/Elev= 30
       0 1695.08    19.3 1693.37      29 1692.72    38.6 1691.87    57.9 1689.73
    67.6 1688.78    77.2 1688.08    86.9 1687.64   106.2 1687.15   135.1 1686.99
   144.8 1686.75   154.4 1686.08   173.7  1683.7     193 1680.89   202.7 1679.95
   212.4 1679.96   215.2 1680.38     222 1681.41   231.6 1683.87     251 1688.16
   260.6 1690.45   270.3 1692.94   279.9 1695.61   289.6 1698.53   308.9 1704.66
   318.5  1707.4   328.2 1709.63   337.8 1711.66   357.1 1715.18   386.1 1719.42
#Mann= 3 , 0 , 0
       0      .1       0     193    .045       0   215.2      .1       0
Bank Sta=193,215.2
XS Rating Curve= 0 ,0
Exp/Cntr=0.3,0.1

Type RM Length L Ch R = 1 ,15779.8 ,806,784.8,763.2
XS GIS Cut Line= 2
     1939070.669      392751.593     1938710.426      392617.045
#Sta/Elev= 29
       0 1706.07    19.2 1704.65    86.5 1699.27    96.1 1698.34   105.8 1696.35
   115.4 1692.76   134.6 1683.68   144.2 1680.36   153.8 1678.88   163.4 1678.58
   182.7 1678.72   192.3 1678.66   201.9 1678.26   211.5 1677.56   221.1 1676.35
   230.7 1674.74   234.5 1674.25   240.3 1673.51     250 1673.29   259.6 1674.28
   269.2  1676.2   288.4 1680.52     298 1682.54   307.6 1684.74   317.2 1687.11
   326.9 1689.55   336.5 1692.11   365.3 1700.14   384.6 1705.32
#Mann= 3 , 0 , 0
       0      .1       0   234.5    .045       0   259.6      .1       0
Bank Sta=234.5,259.6
XS Rating Curve= 0 ,0
Exp/Cntr=0.3,0.1

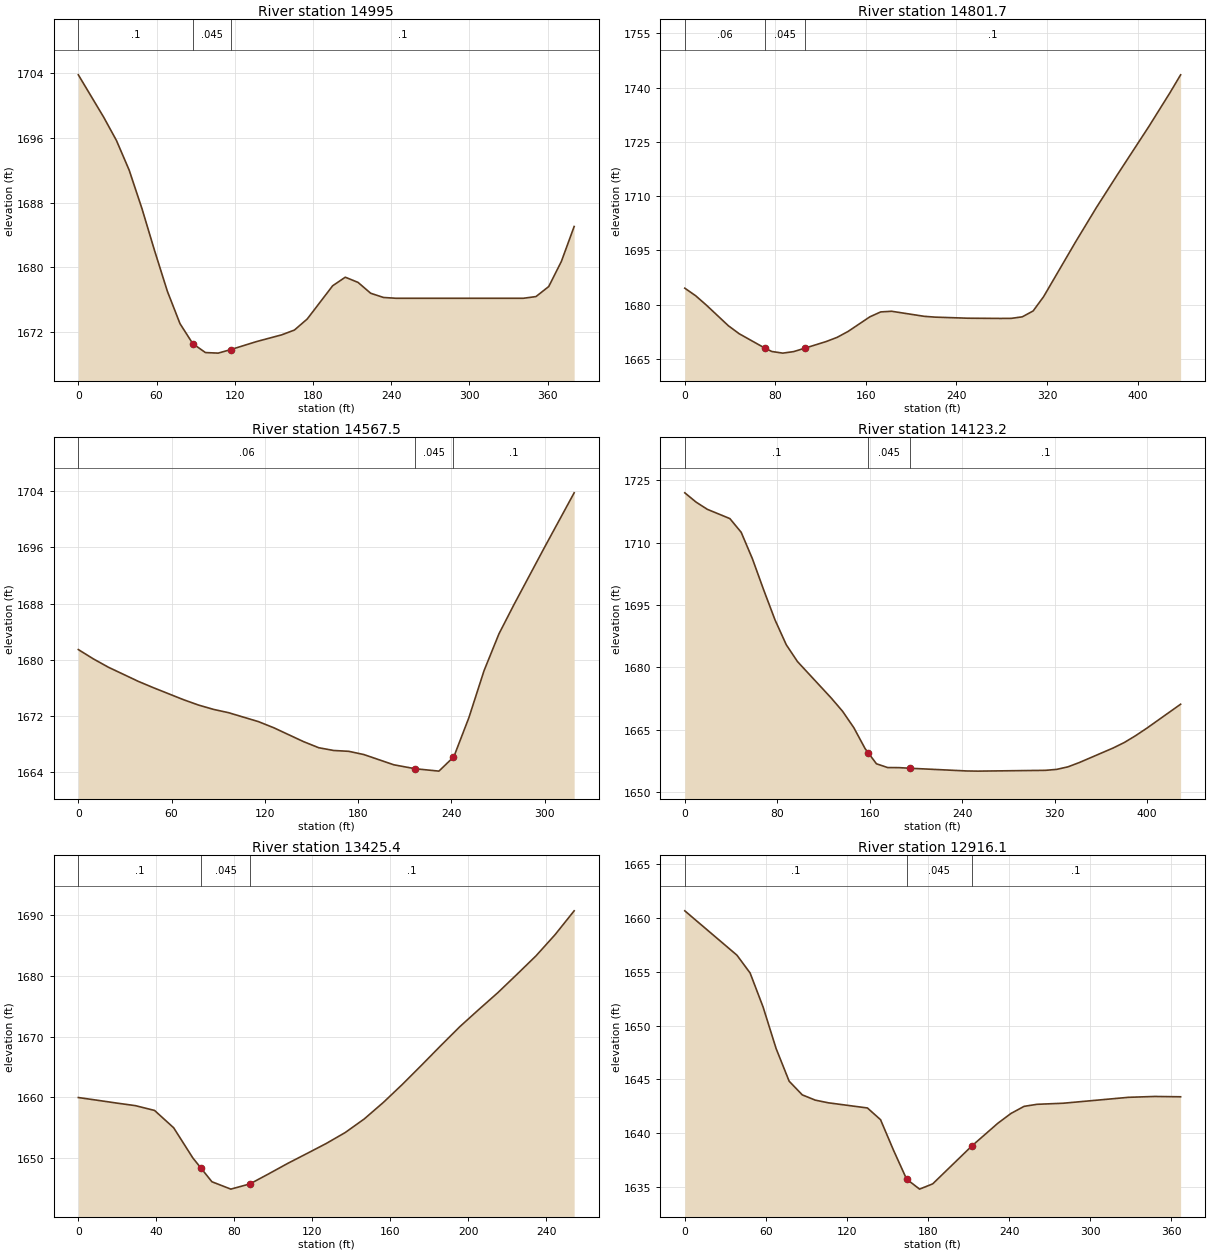
Type RM Length L Ch R = 1 ,14995   ,201.4,193.4,185.2
XS GIS Cut Line= 2
     1939038.117      391866.177     1938721.277       392076.68
#Sta/Elev= 27
       0 1703.78    19.5 1698.54    29.3 1695.66      39 1692.02    48.8 1687.28
    58.5 1682.08    68.3 1677.07      78 1673.07    87.8  1670.6    97.5  1669.5
   107.3 1669.43     117 1669.87   136.6 1670.85   156.1 1671.69   165.8 1672.28
   175.6 1673.64   195.1 1677.74   204.8  1678.8   214.6 1678.16   224.3 1676.82
   234.1  1676.3   243.8  1676.2   341.4  1676.2   351.1 1676.41   360.9 1677.65
   370.6 1680.75   380.4 1685.06
#Mann= 3 , 0 , 0
       0      .1       0    87.8    .045       0     117      .1       0
Bank Sta=87.8,117
XS Rating Curve= 0 ,0
Exp/Cntr=0.3,0.1

Type RM Length L Ch R = 1 ,14801.7 ,210,234.2,258.5
XS GIS Cut Line= 3
     1938855.085      391736.364     1938674.963       391985.93
     1938562.116      392051.034
#Sta/Elev= 30
       0 1684.56     9.6 1682.47    19.2 1679.84    38.5 1674.18    48.1 1671.96
    70.9 1667.97    76.9 1667.06    86.6 1666.61    96.2 1667.03   105.8 1667.95
     125 1669.82   134.6 1670.97   144.3 1672.61   163.5 1676.64   173.1    1678
   182.7 1678.18   211.6 1676.78   221.2 1676.56   250.1 1676.26   278.9  1676.2
   288.5 1676.22   298.2 1676.64   307.8 1678.27   317.1 1682.25     345  1697.2
   363.6 1706.81   382.2 1715.91   410.1 1729.28   428.8 1738.64   438.1 1743.53
#Mann= 3 , 0 , 0
       0     .06       0    70.9    .045       0   105.8      .1       0
Bank Sta=70.9,105.8
XS Rating Curve= 0 ,0
Exp/Cntr=0.3,0.1

Type RM Length L Ch R = 1 ,14567.5 ,452.7,444.2,435.8
XS GIS Cut Line= 2
     1938857.996      391683.885     1938541.155      391646.993
#Sta/Elev= 27
       0 1681.44     9.7 1680.11    19.3 1678.93    38.7  1676.9    48.3 1676.01
    67.7  1674.3    77.3 1673.54      87 1672.92    96.7 1672.45     116 1671.17
   125.7 1670.31     145 1668.32   154.7 1667.46   164.3 1667.07     174 1666.95
   183.7 1666.49     203 1665.03   216.7 1664.47     232 1664.13   241.31666.116
   241.6 1666.18   251.3 1671.76     261 1678.42   270.6 1683.67   280.3 1687.85
   299.6 1695.86     319 1703.76
#Mann= 3 , 0 , 0
       0     .06       0   216.7    .045       0   241.3      .1       0
Bank Sta=216.7,241.3
XS Rating Curve= 0 ,0
Exp/Cntr=0.3,0.1

Type RM Length L Ch R = 1 ,14123.2 ,702,697.8,693.6
XS GIS Cut Line= 2
     1938990.374      391245.517     1938575.878      391356.194
#Sta/Elev= 30
       0 1722.01     9.8 1719.77    19.5 1718.04      39 1715.81    48.8 1712.51
    58.5 1706.14    68.2 1698.69      78 1691.47    87.8 1685.45    97.5  1681.4
   126.8  1672.6   136.5 1669.45   146.3 1665.47     156 1660.46   158.6 1659.49
   165.8 1656.81   175.5  1655.9   185.3 1655.88     195 1655.73   243.8 1655.08
   253.5 1655.04     312 1655.23   321.8 1655.46   331.5 1656.07   341.3  1657.1
   370.5 1660.59   380.3 1661.93     390 1663.56   399.8 1665.38     429 1671.14
#Mann= 3 , 0 , 0
       0      .1       0   158.6    .045       0     195      .1       0
Bank Sta=158.6,195
XS Rating Curve= 0 ,0
Exp/Cntr=0.3,0.1

Type RM Length L Ch R = 1 ,13425.4 ,526.2,509.3,492.4
XS GIS Cut Line= 2
     1938434.819       390828.85     1938206.954      390941.698
#Sta/Elev= 29
       0 1659.97     9.8 1659.52    19.6 1659.06    29.3 1658.63    39.1 1657.84
    48.9 1654.98    58.7 1650.02    62.9 1648.33    68.5 1646.08    77.9  1644.9
    78.2 1644.86      88 1645.72    97.8 1647.41   107.6 1649.14   117.4 1650.76
   127.1 1652.38   136.9  1654.2   146.7 1656.45   156.5 1659.18   166.3 1662.17
     176 1665.29   185.8  1668.5   195.6 1671.64   205.4 1674.49   215.2 1677.28
   224.9 1680.27   234.7 1683.33   244.5 1686.83   254.3 1690.77
#Mann= 3 , 0 , 0
       0      .1       0    62.9    .045       0      88      .1       0
Bank Sta=62.9,88
XS Rating Curve= 0 ,0
Exp/Cntr=0.3,0.1

Type RM Length L Ch R = 1 ,12916.1 ,432.7,433,433.2
XS GIS Cut Line= 2
     1938120.148      390294.996      1937989.94      390637.878
#Sta/Elev= 24
       0 1660.67    38.6 1656.54    48.3 1654.89    57.9 1651.73    67.6 1647.84
    77.2 1644.82    86.9 1643.55    96.5 1643.06   106.2 1642.81   135.1 1642.33
   144.8 1641.24   154.4  1638.4   164.1 1635.71   173.7 1634.78   183.4 1635.27
   212.3 1638.79   231.6 1640.91   241.3 1641.82     251 1642.48   260.6 1642.67
   279.9 1642.77   328.2 1643.32   347.5  1643.4   366.8 1643.37
#Mann= 3 , 0 , 0
       0      .1       0   164.1    .045       0   212.3      .1       0
Bank Sta=164.1,212.3
XS Rating Curve= 0 ,0
Exp/Cntr=0.3,0.1