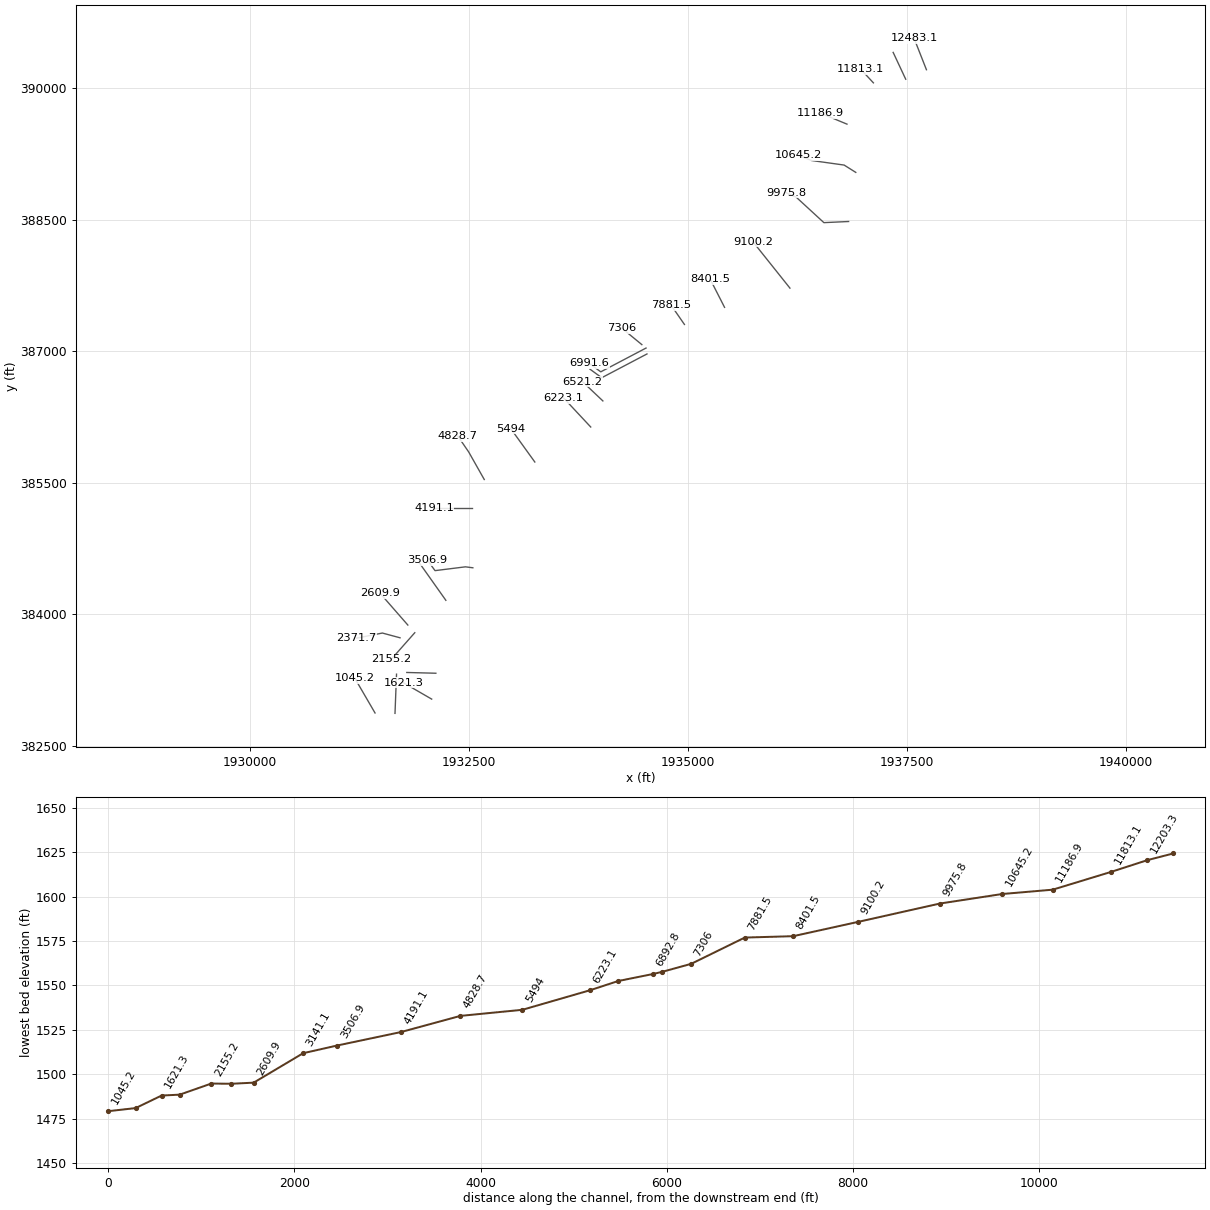
HEC-RAS study MUDDYCK2.prj: MUDDYCK2

--- MUDDYCK2.g01 (geometry) --- (continued)

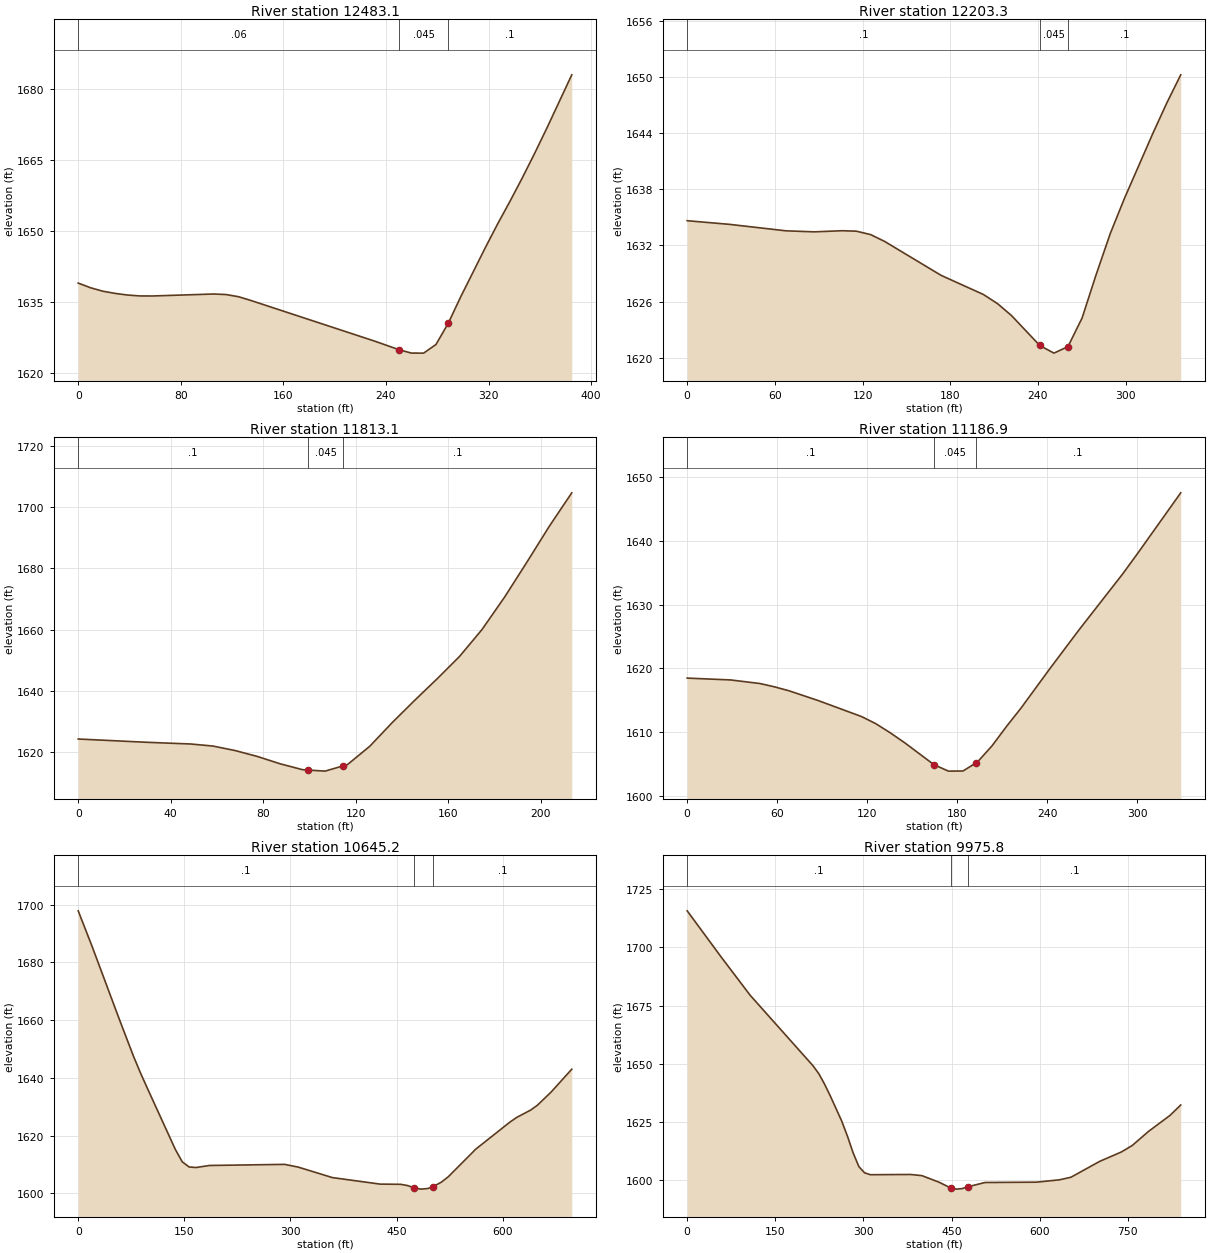
Type RM Length L Ch R = 1 ,12483.1 ,278.4,279.8,281.1
XS GIS Cut Line= 2
     1937725.183      390212.531     1937584.124      390570.604
#Sta/Elev= 25
       0 1639.08     9.6 1638.09    19.2 1637.36    28.9 1636.89    38.5 1636.55
    48.1 1636.36    57.7 1636.35   105.8 1636.77   115.5 1636.65   125.1 1636.19
   134.7  1635.4   230.9 1626.84   250.2    1625   259.8 1624.29   269.4 1624.28
     279  1626.1   288.6  1630.6   298.3 1636.18   317.5 1646.57   327.1 1651.58
   336.8 1656.39   346.4 1661.34     356 1666.51   365.6 1671.88   384.9 1683.07
#Mann= 3 , 0 , 0
       0     .06       0   250.2    .045       0   288.6      .1       0
Bank Sta=250.2,288.6
XS Rating Curve= 0 ,0
Exp/Cntr=0.3,0.1

Type RM Length L Ch R = 1 ,12203.3 ,383.1,390.2,397.3
XS GIS Cut Line= 2
     1937488.638      390104.024     1937345.409      390410.014
#Sta/Elev= 22
       0 1634.64      29 1634.25    67.6 1633.56    86.9 1633.45   106.2 1633.57
   115.8 1633.52   125.5 1633.16   135.1 1632.43   173.8  1628.8   202.7 1626.76
   212.4 1625.78     222  1624.5   241.3 1621.31     251 1620.49   260.6 1621.18
   270.3 1624.25   279.9 1628.88   289.6 1633.28   299.2    1637   318.6 1643.93
   328.2  1647.2   337.8 1650.23
#Mann= 3 , 0 , 0
       0      .1       0   241.3    .045       0   260.6      .1       0
Bank Sta=241.3,260.6
XS Rating Curve= 0 ,0
Exp/Cntr=0.3,0.1

Type RM Length L Ch R = 1 ,11813.1 ,616.4,626.2,635.9
XS GIS Cut Line= 2
     1937119.714      390062.791     1936974.315      390219.041
#Sta/Elev= 25
       0 1624.34     9.7 1623.99    19.4 1623.64    29.1 1623.29    38.8    1623
    48.5 1622.72    58.2 1622.05    67.9 1620.57    77.6 1618.62    87.3 1616.26
      97 1614.34    99.4 1614.22   106.7 1613.87   114.4 1615.55   116.4 1615.99
   126.1    1622   135.8 1629.72   145.5 1636.96   155.2 1643.98   164.9 1651.28
   174.6 1660.05   184.3 1670.54     194 1681.99   203.7 1693.71   213.4  1704.6
#Mann= 3 , 0 , 0
       0      .1       0    99.4    .045       0   114.4      .1       0
Bank Sta=99.4,114.4
XS Rating Curve= 0 ,0
Exp/Cntr=0.3,0.1

Type RM Length L Ch R = 1 ,11186.9 ,545.4,541.7,543.4
XS GIS Cut Line= 2
     1936818.065      389591.871     1936514.246      389717.739
#Sta/Elev= 23
       0 1618.48      29 1618.19    48.4 1617.63      58 1617.12    67.7  1616.5
      87 1614.98   116.1 1612.45   125.7 1611.32   135.4 1609.88   145.1  1608.3
   164.4 1604.89   174.1 1603.87   183.8 1603.89   192.2 1605.12   193.4 1605.29
   203.1 1607.83   212.8 1610.89   222.5 1613.78   241.8    1620   261.2 1626.08
   290.2 1634.84   299.8 1637.94   328.9 1647.58
#Mann= 3 , 0 , 0
       0      .1       0   164.4    .045       0   192.2      .1       0
Bank Sta=164.4,192.2
XS Rating Curve= 0 ,0
Exp/Cntr=0.3,0.1

Type RM Length L Ch R = 1 ,10645.2 ,672.9,669.4,660.3
XS GIS Cut Line= 4
     1936918.366      389041.589     1936785.554      389124.922
     1936413.158      389177.006     1936259.512      389236.901
#Sta/Elev= 30
       0 1697.91    19.6 1685.59    58.8 1659.87    78.4 1647.34    88.2 1641.62
      98 1636.27   137.2 1615.26     147 1610.92   156.8 1609.12   166.4 1608.93
   185.7 1609.64   291.8 1610.02   311.1 1609.07   359.3 1605.44   426.8 1603.18
   455.7 1603.11   465.3 1602.69     475  1601.9   484.6 1601.44   494.2 1601.65
   501.5 1602.27   513.5 1603.88   523.2 1605.74   561.9 1615.28   610.4  1624.7
   620.1 1626.33   639.5 1628.83   649.2 1630.54   668.6 1635.11   697.7 1643.01
#Mann= 3 , 0 , 0
       0      .1       0     475    .045       0   501.5      .1       0
Bank Sta=475,501.5
XS Rating Curve= 0 ,0
Exp/Cntr=0.3,0.1

Type RM Length L Ch R = 1 ,9975.8  ,878.5,875.5,872.3
XS GIS Cut Line= 4
     1936836.856      388481.156     1936554.737      388468.135
     1936238.638      388758.538     1936121.451      388810.621
#Sta/Elev= 30
       0 1715.74    58.4 1695.69   107.1 1679.46   214.2  1649.1     224 1645.71
   233.7 1641.26   243.5 1636.17   262.9 1625.38   272.7 1618.86   282.4 1611.67
   292.2 1605.74   301.9 1603.08   311.7 1602.27     380 1602.37   399.5 1601.87
   428.8 1599.03   448.3 1596.58     458 1596.07   467.8 1596.29   477.5 1597.07
   506.8 1598.92   594.6 1599.06   633.6 1600.08   653.1 1601.18   701.9    1608
   739.1 1612.07   757.5 1614.86     785 1620.87   821.6 1627.77   839.9 1632.24
#Mann= 3 , 0 , 0
       0      .1       0   448.3    .045       0   477.5      .1       0
Bank Sta=448.3,477.5
XS Rating Curve= 0 ,0
Exp/Cntr=0.3,0.1

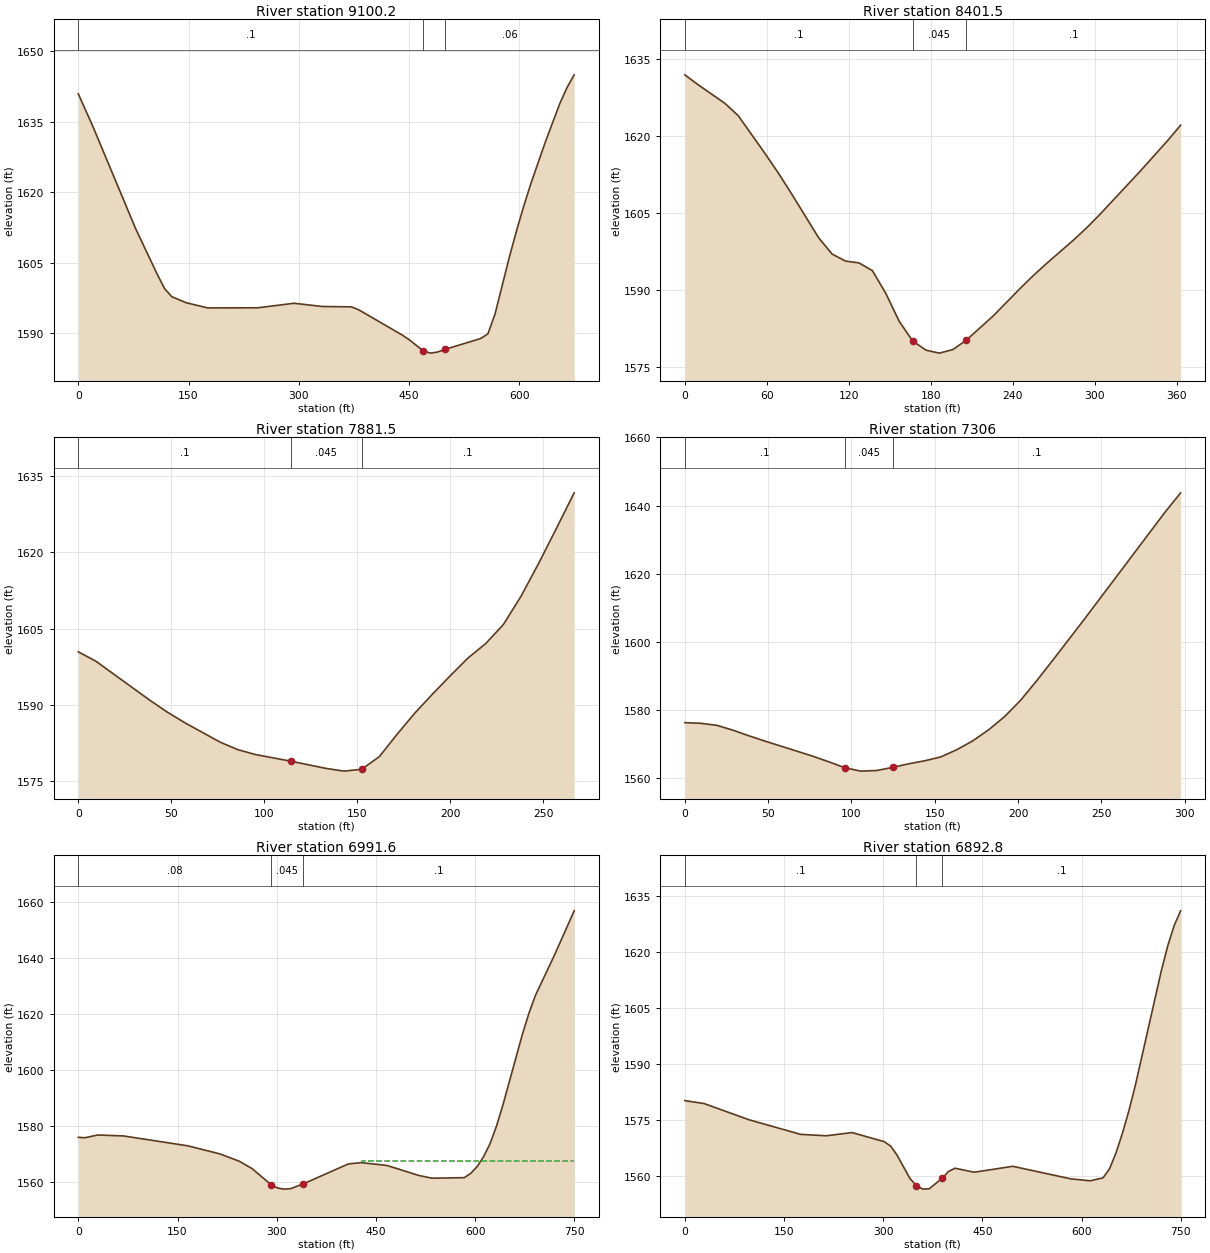
Type RM Length L Ch R = 1 ,9100.2  ,703.2,698.7,694.2
XS GIS Cut Line= 2
     1936167.023      387721.211     1935746.017      388248.555
#Sta/Elev= 30
       0  1640.9    19.6 1634.04    78.2 1612.17   107.6 1602.47   117.4  1599.5
   127.1 1597.79   146.7  1596.5     176 1595.39   244.5 1595.42   293.4 1596.38
   332.5 1595.69   371.6 1595.62   381.4 1595.01   440.1 1589.69   449.9 1588.68
   469.4 1586.26   479.2 1585.78     489 1586.02   498.8 1586.56   547.6 1588.89
   557.4 1589.88   567.2 1594.14   586.8 1606.32   596.6 1611.92   606.3 1617.08
   616.1 1621.92   635.7 1630.72   655.2 1638.81     665 1642.21   674.8 1644.95
#Mann= 3 , 0 , 0
       0      .1       0   469.4    .045       0   498.8     .06       0
Bank Sta=469.4,498.8
XS Rating Curve= 0 ,0
Exp/Cntr=0.3,0.1

Type RM Length L Ch R = 1 ,8401.5  ,517,520,523.1
XS GIS Cut Line= 2
     1935420.496      387502.027     1935255.565      387825.378
#Sta/Elev= 29
       0 1631.93     9.8 1629.99    29.4 1626.37    39.2 1623.95    58.9 1616.54
    68.7 1612.71    78.5 1608.61    98.1 1600.14   107.9    1597   117.7 1595.64
   127.5 1595.29   137.4 1593.76   147.2 1589.33     157 1583.89   166.8 1580.09
   176.6 1578.28   186.4 1577.71   196.2  1578.4     206 1580.21   225.6 1584.91
   245.3 1590.25   255.1 1592.81   264.9 1595.19   284.5 1599.72   294.3 1602.14
   304.1 1604.79   333.6 1613.21   353.2 1619.03     363 1622.11
#Mann= 3 , 0 , 0
       0      .1       0   166.8    .045       0     206      .1       0
Bank Sta=166.8,206
XS Rating Curve= 0 ,0
Exp/Cntr=0.3,0.1

Type RM Length L Ch R = 1 ,7881.5  ,569.3,575.5,581.8
XS GIS Cut Line= 2
     1934962.596      387306.715     1934810.687      387525.899
#Sta/Elev= 24
       0 1600.43     9.5 1598.57    38.1 1590.99    47.6 1588.62    57.2 1586.48
    76.2 1582.65    85.7 1581.17    95.2  1580.2   114.3 1578.89   133.3 1577.46
   142.9 1576.93   152.4 1577.29   161.9 1579.78   171.4 1584.16     181 1588.36
   190.5  1592.1     200  1595.7   209.5 1599.18   219.1 1602.05   228.6 1605.79
   238.1 1611.36   247.6 1617.85   257.2 1624.77   266.7 1631.75
#Mann= 3 , 0 , 0
       0      .1       0   114.3    .045       0   152.4      .1       0
Bank Sta=114.3,152.4
XS Rating Curve= 0 ,0
Exp/Cntr=0.3,0.1

Type RM Length L Ch R = 1 ,7306    ,278.8,314.3,345.8
XS GIS Cut Line= 2
     1934476.485       387076.68     1934246.451      387265.482
#Sta/Elev= 25
       0 1576.35     9.6 1576.16    19.2 1575.57    28.8 1574.16    38.4 1572.51
      48 1570.96    76.8 1566.52    86.4 1564.88      96 1563.14   105.6 1562.14
   115.2 1562.32   124.8 1563.23   134.4 1564.29     144 1565.17   153.6  1566.3
   163.2  1568.4   172.8    1571   182.4 1574.27     192 1578.15   201.6 1582.94
   211.2 1588.63   220.8 1594.61     240 1606.79     288  1637.9   297.6 1643.73
#Mann= 3 , 0 , 0
       0      .1       0      96    .045       0   124.8      .1       0
Bank Sta=96,124.8
XS Rating Curve= 0 ,0
Exp/Cntr=0.3,0.1

Type RM Length L Ch R = 1 ,6991.6  ,100.3,98.8,105.2
XS GIS Cut Line= 3
     1934524.228      387037.618     1934007.735       386766.35
     1933873.187      386864.007
#Sta/Elev= 30
       0 1576.09     9.7 1575.92    29.2 1576.91    68.1 1576.58   165.3 1573.06
   213.9 1570.18   243.1 1567.58   262.5 1564.95   291.7 1559.13   301.4 1557.98
   311.1  1557.6   320.9 1557.77   340.3 1559.49   408.4  1566.6   427.8 1567.04
   466.7 1566.04   515.3 1562.44   534.8  1561.5   583.4 1561.69   593.2 1563.21
     603 1565.67   612.7 1569.17   622.5 1573.86   632.3 1580.16   642.1 1587.77
   671.4 1612.88   681.2 1620.32     691 1626.69   720.3 1641.32   749.6 1656.89
#Mann= 3 , 0 , 0
       0     .08       0   291.7    .045       0   340.3      .1       0
#XS Ineff= 2 , 0
                          428.17         1567.77
Permanent Ineff=
       F       F
Bank Sta=291.7,340.3
XS Rating Curve= 0 ,0
Exp/Cntr=0.3,0.1

Type RM Length L Ch R = 1 ,6892.8  ,407.3,371.7,332.1
XS GIS Cut Line= 3
     1934535.079      386970.343     1934018.586      386699.076
     1933884.037      386796.732
#Sta/Elev= 30
       0 1580.13    29.2 1579.34    97.2 1574.99     175 1571.08   213.9  1570.7
   252.8 1571.56   301.4 1569.13   311.1 1567.95   320.9 1565.51   340.3 1559.27
     350 1557.36   359.8 1556.39   369.5 1556.48   388.9 1559.28   398.6  1561.1
   408.4    1562   437.6 1560.92   495.9 1562.51   583.4 1559.15   612.7 1558.62
   632.3 1559.41   642.1 1561.83   651.8 1566.04   661.6 1571.36   671.4 1577.41
   681.2 1584.26   720.3 1614.86   730.1 1621.62   739.9  1627.1   749.6 1631.03
#Mann= 3 , 0 , 0
       0      .1       0     350    .045       0   388.9      .1       0
Bank Sta=350,388.9
XS Rating Curve= 0 ,0
Exp/Cntr=0.3,0.1

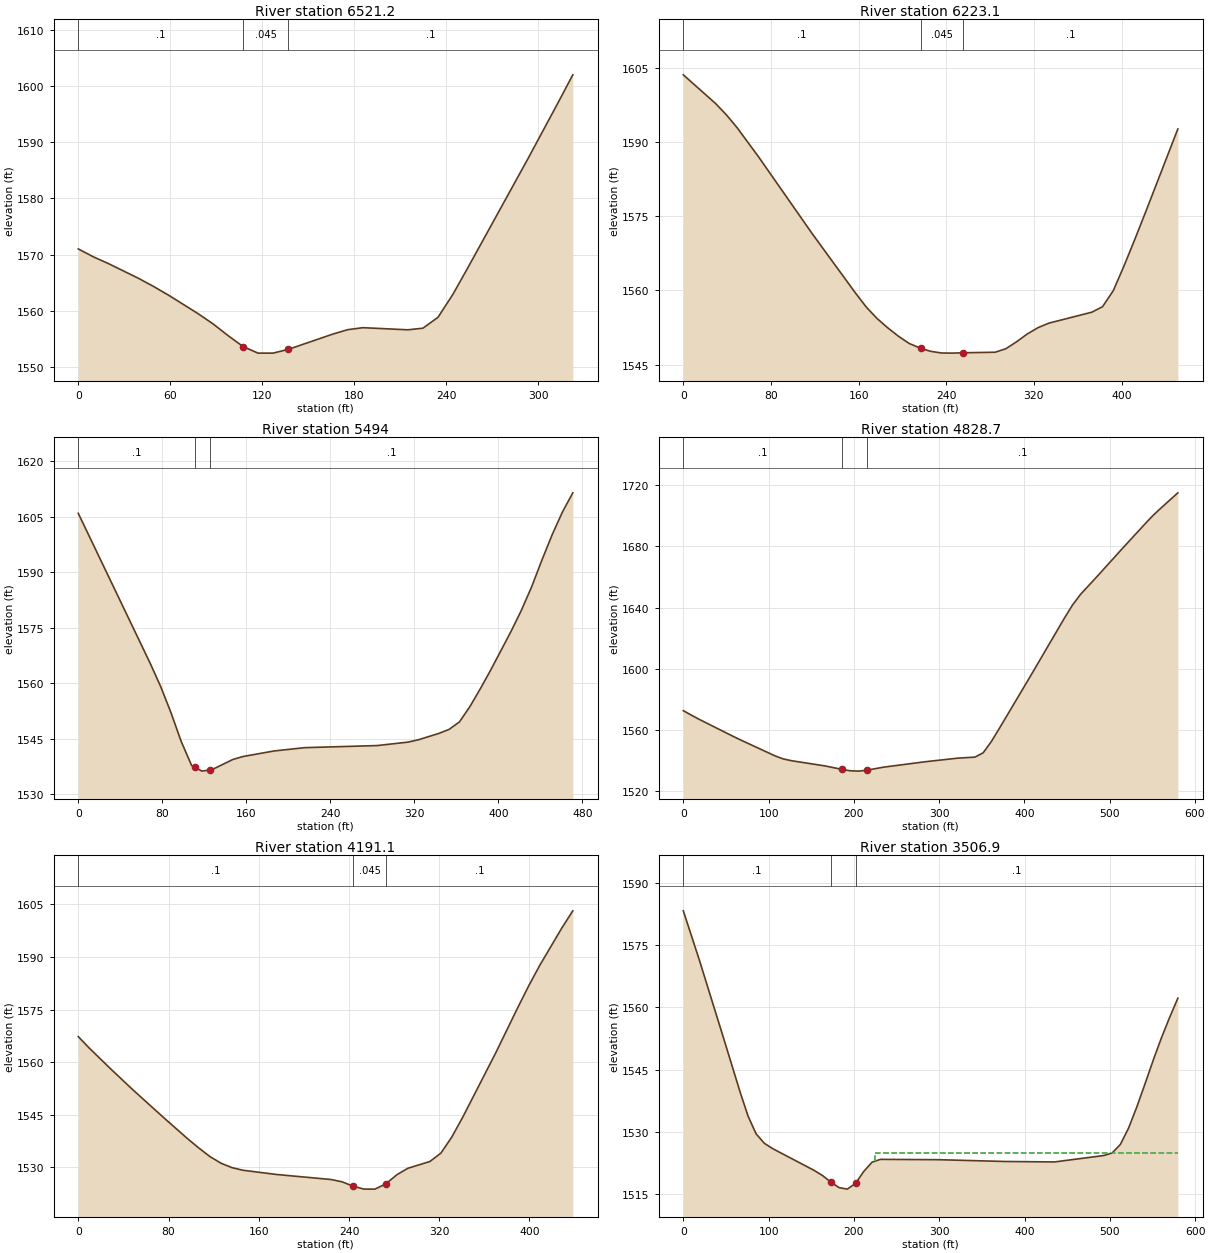
Type RM Length L Ch R = 1 ,6521.2  ,299.4,298,296.6
XS GIS Cut Line= 2
     1934031.607      386434.319     1933797.232      386655.673
#Sta/Elev= 24
       0 1571.01     9.8 1569.61    19.5 1568.42    39.1  1565.8    48.8 1564.37
    58.6 1562.82    78.2 1559.47    87.9 1557.66    97.7 1555.57   107.5 1553.62
   117.2 1552.46     127 1552.46   136.8 1553.12   166.1 1555.86   175.8 1556.64
   185.6 1556.99   214.9 1556.61   224.7  1556.9   234.5 1558.83   244.2 1562.91
     254 1567.67   293.1 1587.04   312.6 1596.94   322.4    1602
#Mann= 3 , 0 , 0
       0      .1       0   107.5    .045       0   136.8      .1       0
Bank Sta=107.5,136.8
XS Rating Curve= 0 ,0
Exp/Cntr=0.3,0.1

Type RM Length L Ch R = 1 ,6223.1  ,731.9,729.1,726.3
XS GIS Cut Line= 2
     1933892.718       386137.01     1933584.558      386466.871
#Sta/Elev= 30
       0 1603.61    29.4 1597.82    39.2 1595.55    49.1 1592.92    68.7 1587.02
   117.8 1571.44     157 1559.53   166.8  1556.7   176.6 1554.38   186.4 1552.48
   196.3 1550.76   206.1 1549.29   217.1 1548.27   225.7  1547.7   235.5 1547.36
   245.3 1547.33   255.1  1547.4   284.6 1547.51   294.4 1548.22   304.2 1549.62
     314 1551.21   323.8 1552.48   333.6 1553.39   372.9 1555.61   382.7 1556.73
   392.5 1559.98   402.3 1564.99   412.2 1570.38     422 1575.88   451.4 1592.67
#Mann= 3 , 0 , 0
       0      .1       0   217.1    .045       0   255.1      .1       0
Bank Sta=217.1,255.1
XS Rating Curve= 0 ,0
Exp/Cntr=0.3,0.1

Type RM Length L Ch R = 1 ,5494    ,667,665.3,662.7
XS GIS Cut Line= 2
     1933254.697      385737.705     1932979.089      386119.649
#Sta/Elev= 30
       0  1605.9    68.7 1565.28    78.5 1559.12    88.3 1552.07    98.1 1544.26
   107.9 1537.85   110.7 1537.41   117.8 1536.29   125.71536.637   127.6 1536.72
   147.2 1539.43     157 1540.24   186.4 1541.73   215.9 1542.63   284.6 1543.19
     314 1544.12   323.8 1544.74   343.4 1546.47   353.2 1547.56   363.1  1549.6
   372.9 1553.67   382.7 1558.42   392.5 1563.42   412.1 1573.98   421.9 1579.64
   431.8 1586.05   441.6  1593.3   451.4 1600.16   461.2  1606.3     471 1611.43
#Mann= 3 , 0 , 0
       0      .1       0   110.7    .045       0   125.7      .1       0
Bank Sta=110.7,125.7
XS Rating Curve= 0 ,0
Exp/Cntr=0.3,0.1

Type RM Length L Ch R = 1 ,4828.7  ,613.9,637.6,662.1
XS GIS Cut Line= 3
      1932677.44      385538.052     1932499.489      385852.722
     1932375.791      386032.843
#Sta/Elev= 30
       0 1572.48     9.8 1569.41    19.5 1566.54    58.6  1555.6    68.4 1552.97
   107.5 1542.86   117.2 1540.85     127 1539.67   166.1 1536.28   186.5 1533.95
   195.4 1533.11   205.2 1532.86     215 1533.43   234.5 1535.43   283.3 1538.98
   322.4 1541.39     342 1542.03   351.7 1544.88   361.5 1552.45     371 1561.17
     409 1596.87     447 1633.12   456.5  1641.7     466 1648.72     485 1660.18
   513.5  1677.8     542  1695.1   551.5 1700.66     561 1705.58     580 1715.14
#Mann= 3 , 0 , 0
       0      .1       0   186.5    .045       0     215      .1       0
Bank Sta=186.5,215
XS Rating Curve= 0 ,0
Exp/Cntr=0.3,0.1

Type RM Length L Ch R = 1 ,4191.1  ,681.4,684.2,687
XS GIS Cut Line= 2
     1932540.721      385208.191     1932102.353      385208.191
#Sta/Elev= 30
       0 1567.28     9.7 1564.02    29.2 1557.93    48.7 1552.02    77.9 1543.54
    97.4 1538.02   107.2 1535.42   116.9 1533.02   126.6 1531.15   136.4 1529.89
   146.1 1529.15   175.4 1527.96   224.1 1526.51   233.8 1525.87   243.5 1524.62
   253.3 1523.78     263 1523.77   272.8  1525.3   282.5 1527.89   292.2 1529.72
   311.7 1531.65   321.5 1534.05   331.2 1538.66     341  1544.4   370.2 1562.72
   389.7 1575.62   399.4 1581.81   409.1 1587.61   428.6 1598.22   438.4 1603.16
#Mann= 3 , 0 , 0
       0      .1       0   243.5    .045       0   272.8      .1       0
Bank Sta=243.5,272.8
XS Rating Curve= 0 ,0
Exp/Cntr=0.3,0.1

Type RM Length L Ch R = 1 ,3506.9  ,391.1,365.8,340.3
XS GIS Cut Line= 4
     1932547.232      384531.107     1932462.596      384541.958
     1932115.374      384498.555     1932030.739      384615.743
#Sta/Elev= 30
       0 1583.25      19 1571.26    47.4 1552.44    66.4 1539.71    75.8 1533.85
    85.3 1529.53      95 1527.24   104.8 1525.95   153.4 1520.71   163.1 1519.49
   172.8 1517.92   182.5 1516.57   192.2  1516.2     202  1517.6   211.7  1520.5
   221.4 1522.71   231.1 1523.37   299.2 1523.29   376.9 1522.86   435.2 1522.75
   493.1  1524.3   502.7  1524.9   512.4 1526.96     522 1530.89   531.6 1535.96
   541.3 1541.57   550.9 1547.25   560.5 1552.63   570.2 1557.59   579.8 1562.21
#Mann= 3 , 0 , 0
       0      .1       0   172.8    .045       0     202      .1       0
#XS Ineff= 2 , 0
                          224.79         1524.88
Permanent Ineff=
       F       F
Bank Sta=172.8,202
XS Rating Curve= 0 ,0
Exp/Cntr=0.3,0.1

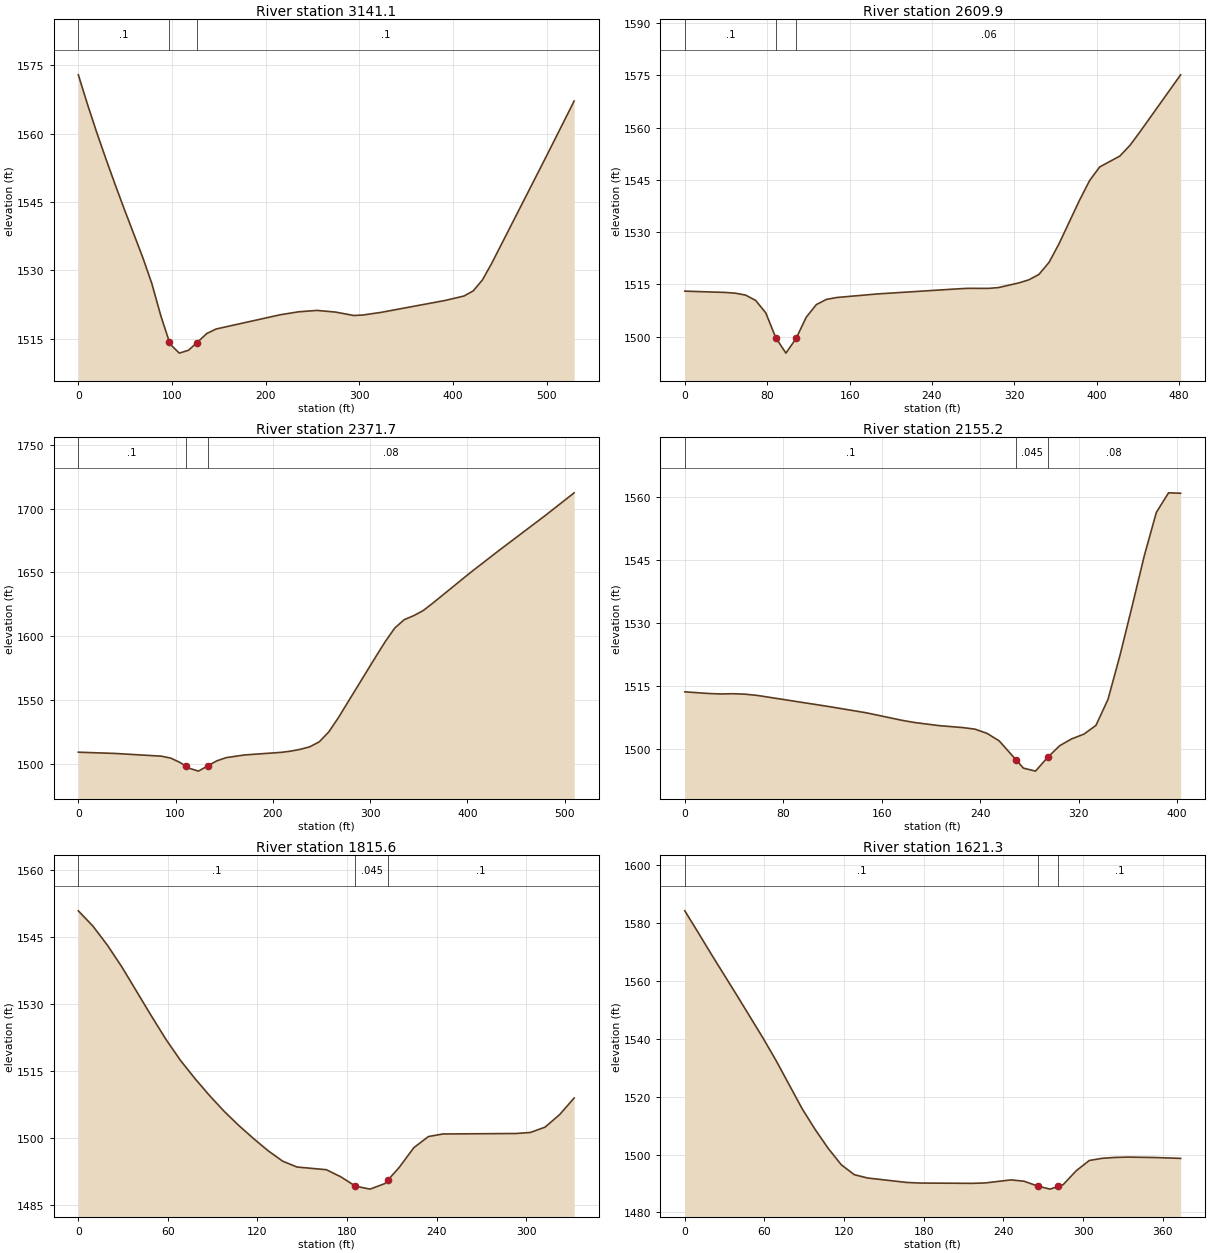
Type RM Length L Ch R = 1 ,3141.1  ,528.8,531.3,533.6
XS GIS Cut Line= 2
     1932239.072      384160.014     1931933.083      384591.871
#Sta/Elev= 30
       0 1572.86     9.8 1566.38    19.6 1560.26    29.4 1554.47    39.2 1548.87
      49 1543.45    68.6 1532.94    78.4 1527.16    88.2 1519.96    97.31514.268
      98 1513.83   107.8 1511.87   117.6  1512.5   126.41514.117   137.2 1516.18
     147 1517.15   215.6 1520.28   235.2 1520.93   254.8 1521.23   274.4 1520.87
     294 1520.12   303.8 1520.22   323.4 1520.81     392 1523.43   411.7 1524.39
   421.5  1525.5   431.3 1527.89   441.1 1531.47   499.9 1555.12   529.3 1567.12
#Mann= 3 , 0 , 0
       0      .1       0    97.3    .045       0   126.4      .1       0
Bank Sta=97.3,126.4
XS Rating Curve= 0 ,0
Exp/Cntr=0.3,0.1

Type RM Length L Ch R = 1 ,2609.9  ,224.6,238.2,251.7
XS GIS Cut Line= 2
     1931805.044      383877.896     1931488.204      384240.309
#Sta/Elev= 30
       0 1513.08    39.3 1512.71    49.1 1512.49      59 1511.95    68.8 1510.42
    78.6 1506.86    88.4 1499.68    98.2  1495.3   108.1 1499.52   117.9  1505.6
   127.7 1509.22   137.5 1510.71   147.4 1511.25   186.7 1512.27   265.2 1513.74
   275.1 1513.89   294.7 1513.86   304.6 1514.11   324.2 1515.43     334 1516.32
   343.8 1517.87   353.7 1521.35   363.5 1526.77   383.1 1539.07     393 1544.78
   402.8  1548.7   422.4 1551.83   432.3 1554.93   442.1 1558.84   481.4 1575.13
#Mann= 3 , 0 , 0
       0      .1       0    88.4    .045       0   108.1     .06       0
Bank Sta=88.4,108.1
XS Rating Curve= 0 ,0
Exp/Cntr=0.3,0.1

Type RM Length L Ch R = 1 ,2371.7  ,191.1,216.5,241.8
XS GIS Cut Line= 3
     1931716.069      383732.496     1931514.246       383786.75
     1931219.107      383728.156
#Sta/Elev= 30
       0 1509.49      38  1508.5    85.5 1506.36      95 1504.87   104.5 1501.47
   110.7 1498.52     114 1496.95   123.5 1494.68     133 1498.75   142.5 1502.74
     152 1505.22     171 1507.33     209 1509.37   218.7 1510.35   228.4 1511.74
   238.1 1513.73   247.8  1517.6   257.5 1525.28   267.2 1536.18     306 1584.28
   315.8 1596.14   325.5 1606.64   335.2 1613.12   344.9 1616.24   354.6 1620.18
   364.3 1625.88   403.1 1649.85   432.2 1666.98   480.8  1694.9   509.9 1712.28
#Mann= 3 , 0 , 0
       0      .1       0   110.7    .045       0     133     .08       0
Bank Sta=110.7,133
XS Rating Curve= 0 ,0
Exp/Cntr=0.3,0.1

Type RM Length L Ch R = 1 ,2155.2  ,359.8,339.6,319.3
XS GIS Cut Line= 2
     1931884.279      383790.449     1931617.352        383488.8
#Sta/Elev= 30
       0 1513.63    19.6 1513.23    29.5 1513.12    39.3 1513.18    49.1 1513.07
      59 1512.77   117.9 1510.09   147.4 1508.65   176.8 1506.84   186.7 1506.34
   206.3 1505.61     226 1505.13   235.8 1504.76   245.6 1503.75   255.4 1501.98
   269.2 1497.44   275.1  1495.5   284.9 1494.79   294.7 1498.04   304.6 1500.84
   314.4 1502.47   324.2 1503.57     334 1505.65   343.8 1511.84   353.7 1522.47
   363.5 1534.09   373.3 1545.98   383.1 1556.27     393 1560.91   402.8 1560.81
#Mann= 3 , 0 , 0
       0      .1       0   269.2    .045       0   294.7     .08       0
Bank Sta=269.2,294.7
XS Rating Curve= 0 ,0
Exp/Cntr=0.3,0.1

Type RM Length L Ch R = 1 ,1815.6  ,205.9,194.3,182.6
XS GIS Cut Line= 2
     1932125.164      383328.209     1931793.133       383336.89
#Sta/Elev= 30
       0 1550.88     9.8 1547.45    19.5 1543.17    29.3 1538.24    48.8 1527.41
    58.6 1522.13    68.4 1517.39    78.2 1513.28    87.9  1509.5    97.7 1505.97
   107.5  1502.8   117.2 1499.92     127 1497.18   136.8 1494.82   146.5  1493.5
   166.1  1492.9   175.8 1491.31   185.6 1489.22   195.4 1488.55   205.2 1489.78
   207.3 1490.56   214.9  1493.4   224.7 1497.83   234.5 1500.33   244.2  1500.9
   293.1 1501.01   302.8 1501.24   312.6 1502.43   322.4 1505.25   332.1 1508.96
#Mann= 3 , 0 , 0
       0      .1       0   185.6    .045       0   207.3      .1       0
Bank Sta=185.6,207.3
XS Rating Curve= 0 ,0
Exp/Cntr=0.3,0.1

Type RM Length L Ch R = 1 ,1621.3  ,303.9,278.6,253.1
XS GIS Cut Line= 2
     1932077.421      383033.071      1931754.07      383219.703
#Sta/Elev= 29
       0 1584.17     9.8 1576.88    19.6 1569.46    39.3 1554.93      59 1540.16
    68.8 1532.41    88.4  1515.8    98.2 1508.62   108.1 1502.06   117.9 1496.43
   127.7 1493.02   137.6 1491.89     167 1490.35   176.8 1490.14   216.2 1490.04
     226 1490.16   245.6 1491.23   255.4 1490.78   266.1 1489.05   275.1 1488.04
   281.1 1488.98   284.9 1489.57   294.8  1494.4   304.6 1497.93   314.4 1498.69
   324.2 1498.99     334  1499.1   353.7 1498.96   373.4 1498.66
#Mann= 3 , 0 , 0
       0      .1       0   266.1    .045       0   281.1      .1       0
Bank Sta=266.1,281.1
XS Rating Curve= 0 ,0
Exp/Cntr=0.3,0.1

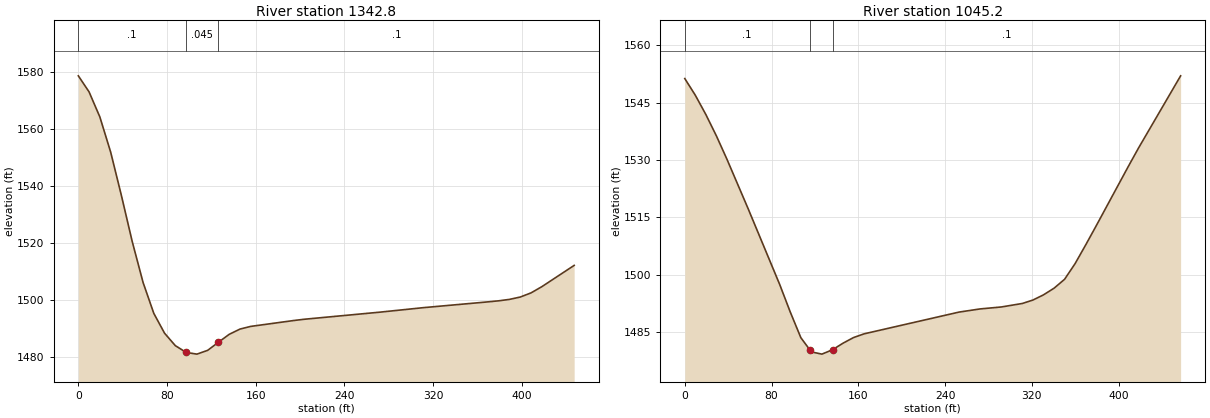
Type RM Length L Ch R = 1 ,1342.8  ,284.6,297.6,310.5
XS GIS Cut Line= 2
     1931658.584       382870.31     1931675.945      383317.359
#Sta/Elev= 28
       0 1578.82     9.7 1573.17    19.4 1564.39    29.2 1551.97    38.9  1536.7
    48.6 1520.61    58.4  1506.2    68.1 1495.32    77.8 1488.35    87.5 1483.98
    97.3 1481.59     107 1480.99   116.7 1482.32   126.4 1485.16   136.2 1487.96
   145.9  1489.8   155.6 1490.74   194.5 1492.81   204.2 1493.26   272.3 1495.75
   311.2 1497.32   369.6 1499.36   379.3 1499.73     389 1500.23   398.8 1501.06
   408.5 1502.52   418.2 1504.69   447.4 1512.18
#Mann= 3 , 0 , 0
       0      .1       0    97.3    .045       0   126.4      .1       0
Bank Sta=97.3,126.4
XS Rating Curve= 0 ,0
Exp/Cntr=0.3,0.1

Type RM Length L Ch R = 1 ,1045.2  ,177.9,200,222
XS GIS Cut Line= 2
      1931430.72       382874.65     1931200.685      383269.616
#Sta/Elev= 30
       0 1551.34     9.7 1546.98    19.4 1541.94    29.2  1536.3    38.9  1530.2
    58.4 1517.28    87.5 1497.44    97.2 1490.26     107 1483.52   115.1 1480.41
   116.7  1479.8   126.4 1479.22   136.2 1480.37   145.9 1482.09   155.6 1483.56
   165.3 1484.53   252.8 1490.22   272.3 1491.05   291.8 1491.56   311.2 1492.48
   320.9 1493.37   330.6 1494.72   340.4 1496.47   350.1  1498.8   359.8  1502.9
   369.6 1507.81   379.3 1512.82   408.4 1528.09   418.2 1533.12   457.1 1552.06
#Mann= 3 , 0 , 0
       0      .1       0   115.1    .045       0   136.2      .1       0
Bank Sta=115.1,136.2
XS Rating Curve= 0 ,0
Exp/Cntr=0.3,0.1