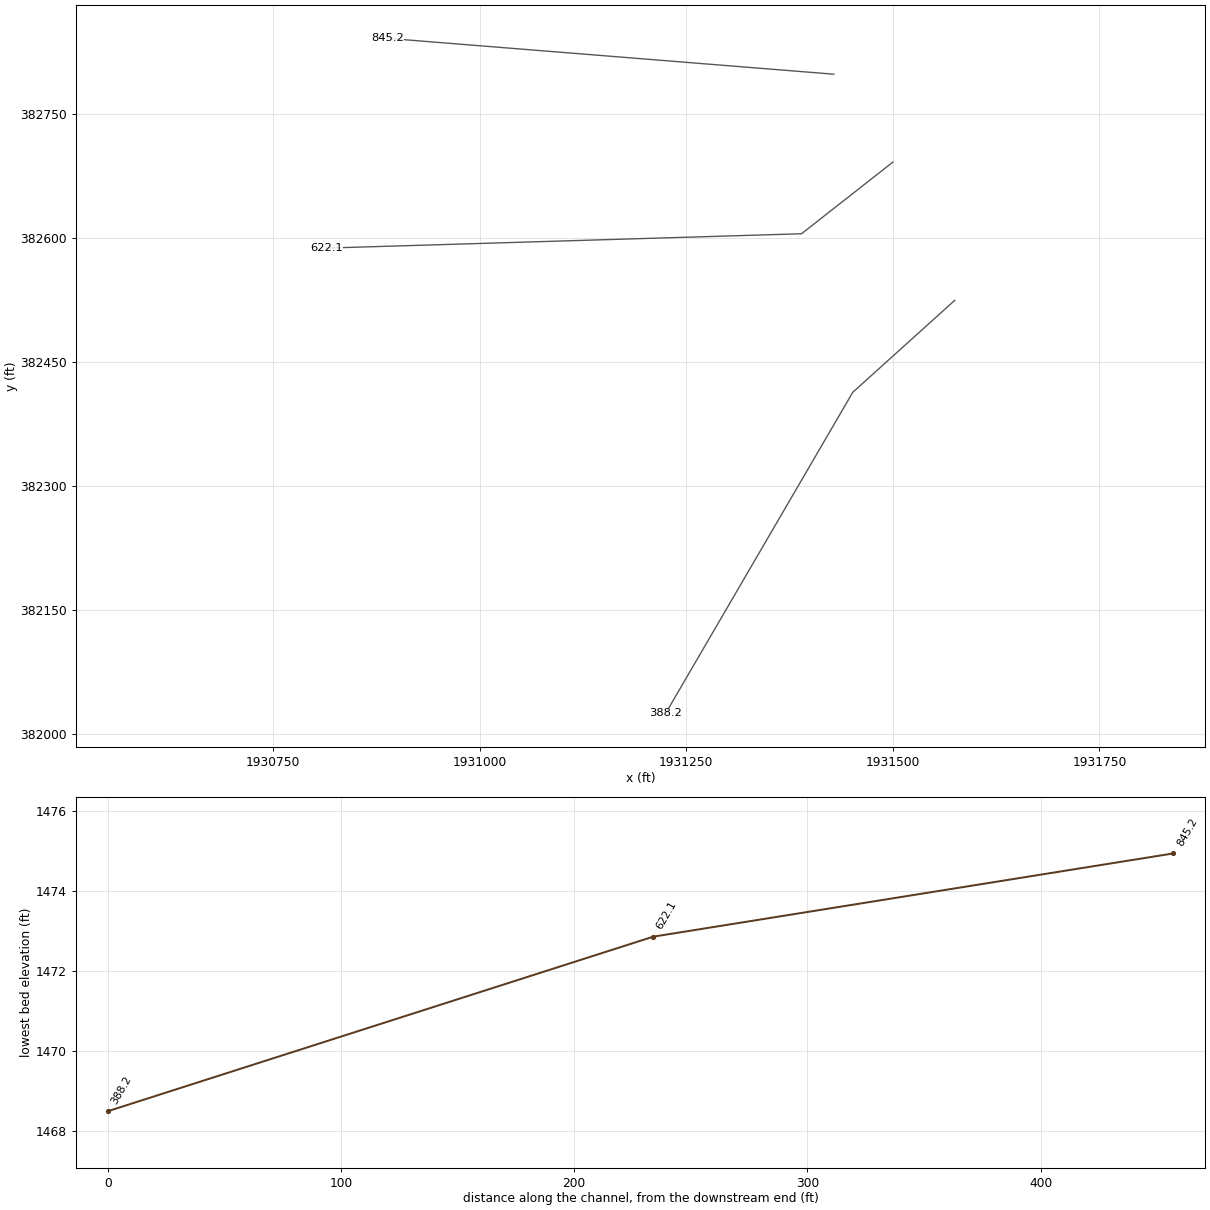
HEC-RAS study MUDDYCK2.prj: MUDDYCK2

--- MUDDYCK2.g01 (geometry) --- (continued)

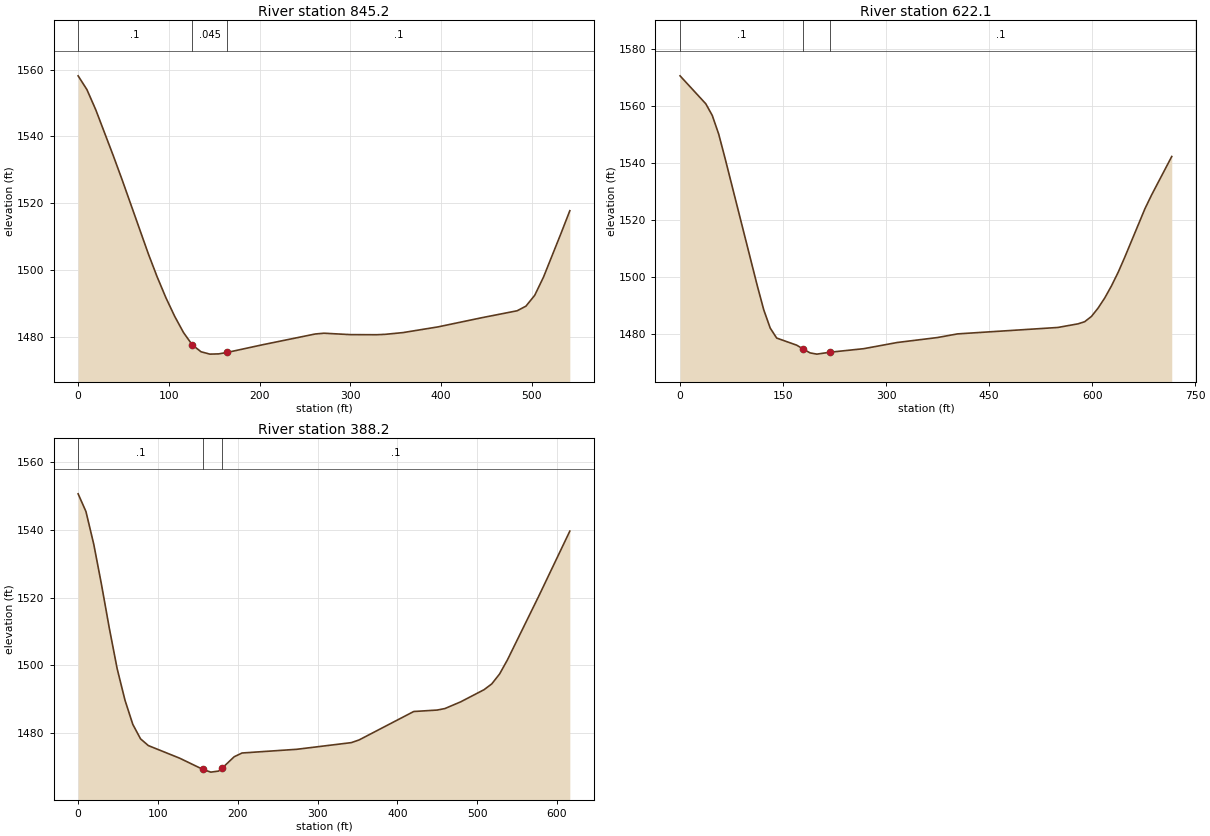
Type RM Length L Ch R = 1 ,845.2   ,220.5,223.1,225.9
XS GIS Cut Line= 2
     1931428.549      382798.696     1930888.185      382842.098
#Sta/Elev= 30
       0 1558.13     9.7 1554.01    19.4 1548.02    38.7  1534.3    48.4 1527.14
    77.4 1504.92    87.1 1498.05    96.8 1491.78   106.5 1486.21   116.2 1481.38
   125.8 1477.71   135.5 1475.64   145.2 1474.93   154.9    1475   164.6 1475.45
   203.3 1477.73   261.4 1480.95     271 1481.18   300.1 1480.76   329.1 1480.73
   338.8 1480.85   358.2 1481.37   396.9 1483.08   445.3 1485.83     484 1487.89
   493.7 1489.27   503.4 1492.52   513.1 1497.97   532.4 1511.04   542.1  1517.8
#Mann= 3 , 0 , 0
       0      .1       0   125.8    .045       0   164.6      .1       0
Bank Sta=125.8,164.6
XS Rating Curve= 0 ,0
Exp/Cntr=0.3,0.1

Type RM Length L Ch R = 1 ,622.1   ,215.6,233.9,257.9
XS GIS Cut Line= 3
     1931500.164      382692.359     1931389.487      382605.553
       1930814.4      382588.192
#Sta/Elev= 30
       0 1570.54    37.5 1560.72    46.9 1556.64    56.3 1550.07    65.6 1541.54
   112.5 1496.83   121.9 1488.39   131.3 1481.99   140.7 1478.49   169.9 1475.99
   179.7 1474.58   189.4 1473.28   199.2 1472.85   218.7 1473.53   267.4 1474.76
   316.2 1476.93   374.7 1478.67     404 1479.95   550.2 1482.21   579.5 1483.48
   589.2 1484.23     599 1486.07   608.7    1489   618.5  1492.6   628.2  1496.8
     638 1501.59   647.7 1506.94     677 1523.92   686.8  1528.8     716 1542.23
#Mann= 3 , 0 , 0
       0      .1       0   179.7    .045       0   218.7      .1       0
Bank Sta=179.7,218.7
XS Rating Curve= 0 ,0
Exp/Cntr=0.3,0.1

Type RM Length L Ch R = 1 ,388.2   ,396.3,388.2,374.1
XS GIS Cut Line= 3
        1931575.         382525.     1931451.516      382413.658
        1931225.         382025.
#Sta/Elev= 30
       0 1550.68     9.8 1545.46    19.6 1535.78    29.3 1523.87    39.1 1510.98
    48.9 1499.05    58.7 1489.75    68.5  1482.6    78.2 1478.32      88 1476.33
   127.2 1472.61   156.5 1469.28   166.3 1468.49     176  1468.8   180.2 1469.61
   195.6 1473.04   205.4 1474.14   273.8 1475.23   342.3  1477.2   352.1    1478
   420.5 1486.39   449.9 1486.82   459.6 1487.27   479.2 1489.23   508.6 1492.83
   518.3 1494.55   528.1 1497.48   537.9 1501.63     577 1520.38   616.1 1539.66
#Mann= 3 , 0 , 0
       0      .1       0   156.5    .045       0   180.2      .1       0
Bank Sta=156.5,180.2
XS Rating Curve= 0 ,0
Exp/Cntr=0.3,0.1

Chan Stop Cuts=-1
Use User Specified Reach Order=0
Composite Channel Slope=5